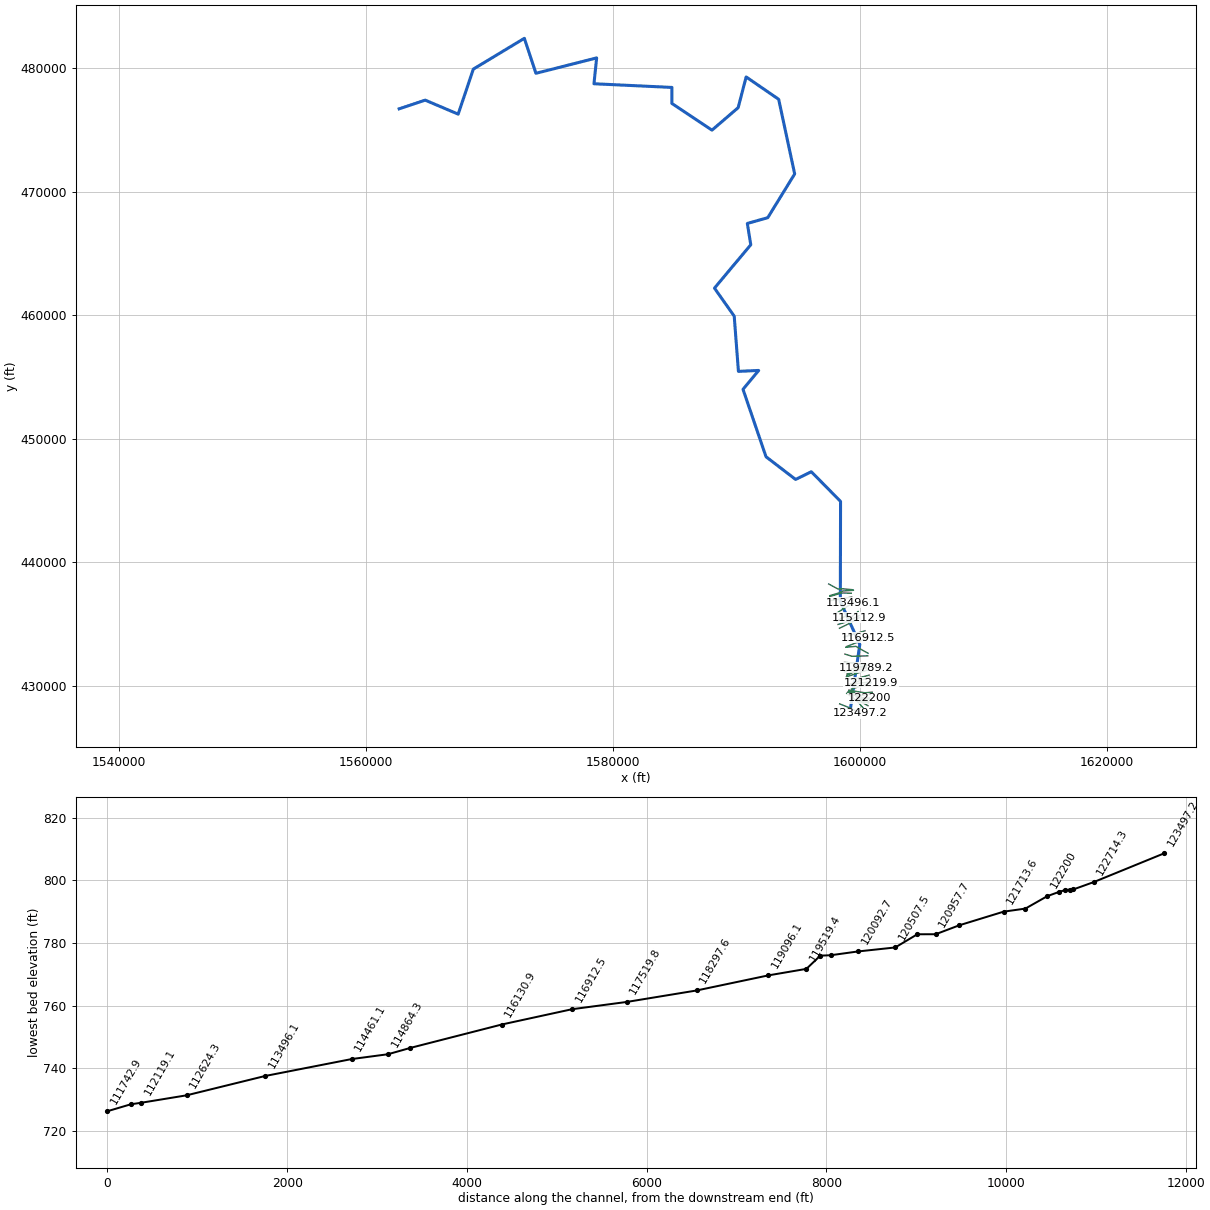
--- BEECHFK.prj (project) ---

Proj Title=BEECHFK
Current Plan=p01
Default Exp/Contr=0,0
English Units
Geom File=g01
Flow File=f01
Plan File=p01
BEGIN DESCRIPTION:
END DESCRIPTION:
DSS Export Rating Curves= 0
DSS Export Rating Curve Sorted= 0
DSS Export Volume Flow Curves= 0
DXF OffsetX= 0
DXF OffsetY= 0
DXF ScaleX= 0
DXF ScaleY= 0

--- BEECHFK.p01 (plan) ---

Plan Title=Floodplain
Program Version=4.00
Geom File=g01
Flow File=f01
K Sum by GR=0
Std Step Tol=0.01
Critical Tol=0.01
Num of Std Step Trials=20
Max Error Tol=0.3
Flow Tol Ratio=0.001
Split Flow NTrial=30
Split Flow Tol=0.02
Split Flow Ratio=0.02
Log Output Level=0
Friction Slope Method=1
Unsteady Friction Slope Method=2
Unsteady Bridges Friction Slope Method=1
Global Log Level=0
CheckData=False
Run HTab=0
Run UNet=0
Run PostProcess=0
UNET Theta=0
UNET Theta Warmup=0
UNET ZTol=0
UNET ZSATol=0
UNET MxIter=0
UNET MaxInSteps=0
UNET DtIC=0
UNET DtMin=0
UNET MaxCRTS=0
UNET WFStab=0
UNET SFStab=0
UNET WFX=0
UNET SFX=0
UNET DSS MLevel=0
UNET DZMax Abort=0
UNET Convert EG Bridges=0
UNET Use Existing IB Tables=0
UNET Froude Limit=0
UNET Froude Power=0
Write IC File=0
Echo Input=False
Echo Output=False
Write Detailed=0

--- BEECHFK.f01 (steady flow) ---

Flow Title=NFF Regression Equation
Program Version=4.00
Number of Profiles= 1
Profile Names=P100yr
River Rch & RM=BEECHFK,Main            ,123497.2
     344
River Rch & RM=BEECHFK,Main            ,121955.6
     374
River Rch & RM=BEECHFK,Main            ,121713.6
     427
River Rch & RM=BEECHFK,Main            ,120753.5
     450
River Rch & RM=BEECHFK,Main            ,120507.5
     611
River Rch & RM=BEECHFK,Main            ,117519.8
     677
River Rch & RM=BEECHFK,Main            ,116912.5
     734
River Rch & RM=BEECHFK,Main            ,115112.9
     812
River Rch & RM=BEECHFK,Main            ,112119.1
     892
River Rch & RM=BEECHFK,Main            ,111742.9
    1153
River Rch & RM=BEECHFK,Main            ,108498.2
    1258
River Rch & RM=BEECHFK,Main            ,106422.9
    1392
River Rch & RM=BEECHFK,Main            ,102495
    1458
River Rch & RM=BEECHFK,Main            ,102181.1
    1694
River Rch & RM=BEECHFK,Main            ,100384.5
    1802
River Rch & RM=BEECHFK,Main            ,92583.9
    1972
River Rch & RM=BEECHFK,Main            ,92267.3
    2608
River Rch & RM=BEECHFK,Main            ,83140.2
    2852
River Rch & RM=BEECHFK,Main            ,74279.4
    3160
River Rch & RM=BEECHFK,Main            ,64408.5
    3458
River Rch & RM=BEECHFK,Main            ,63144.9
    4288
Boundary for River Rch & Prof#=BEECHFK,Main            , 1
Up Type= 0
Dn Type= 3
Dn Slope=0.00033
DSS Import GetInterval= 0
DSS Import GetPeak= 0
DSS Import FillOption= 0

--- BEECHFK.g01 (geometry) ---

Geom Title=USGS 10m DEM
Program Version=4.00

River Reach=BEECHFK         ,Main
Reach XY= 30
     1599235.167      428160.654     1599990.681       433328.67
     1598413.124      436822.244     1598431.962      444913.036
     1596063.065      447317.043     1594789.988       446693.42
     1592392.988      448533.128     1590530.139      453994.238
     1591801.686      455523.375     1590159.224      455446.854
     1589817.539      459921.419     1588219.196      462189.327
     1591159.621      465703.421     1590879.916       467428.72
     1592534.218       467893.85     1594715.082      471438.613
     1593418.876      477485.746     1590784.947      479295.006
     1590136.661      476805.234     1588016.017      474985.303
     1584766.399      477149.409     1584774.995      478445.244
     1578458.486      478743.461     1578674.759      480836.672
     1573758.417      479589.242     1572819.947      482422.028
     1568686.781      479929.163     1567460.299      476281.676
     1564787.606      477416.272     1562681.277      476713.478

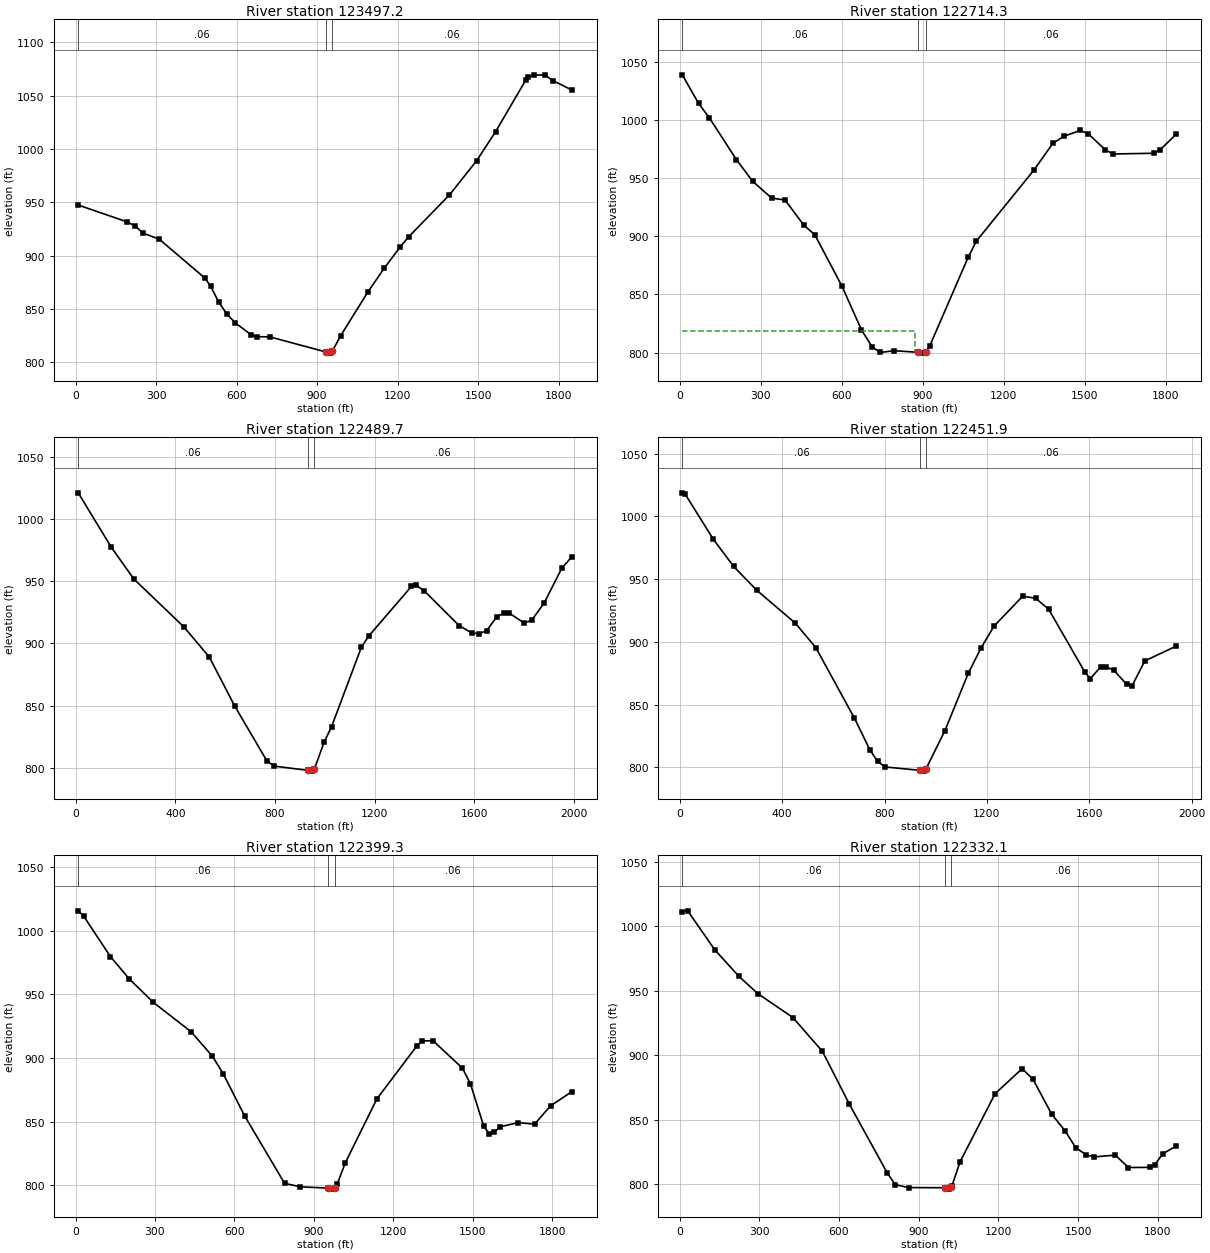
Type RM Length L Ch R = 1 ,123497.2,786,782.9,780.9
XS GIS Cut Line= 3
     1598360.043      428514.348     1599241.697      428168.228
     1600039.558      427746.365
#Sta/Elev= 30
    10.1  947.39   191.4  931.71   221.7  927.88   251.9  921.08   312.4  915.33
   483.7  878.64   503.8   871.1     534  856.34   564.3  845.24   594.5  837.18
     655   825.7   675.1  824.17   725.5   823.8   932.2  809.79   947.2  808.65
   957.3  810.58   987.7  824.86  1089.1  865.78    1150  888.09  1210.8  908.41
  1241.2  917.59  1393.4  956.83  1494.8  988.93  1565.7 1016.23  1677.3 1064.27
  1687.4 1067.44  1707.7 1069.11  1748.3  1069.4  1778.7 1064.07  1849.7 1055.13
#Mann= 3 , 0 , 0
    10.1     .06       0   932.2    .045       0   957.3     .06       0
Bank Sta=932.2,957.3
XS Rating Curve= 0 ,0
Exp/Cntr=0.3,0.1

Type RM Length L Ch R = 1 ,122714.3,226.8,224.6,220.4
XS GIS Cut Line= 4
      1598928.07      429373.837     1599339.577      429071.648
     1599845.768      428665.074     1600292.711      428154.662
#Sta/Elev= 30
      10 1039.08    70.1 1014.51   110.1  1002.1   210.2  966.15   270.3  947.47
   340.4  932.97   390.4  931.28   460.5  909.51   500.5  901.45   601.8  856.88
   672.9  819.74   713.4  804.61   743.9  800.08   794.6  801.53     881  800.21
     896  799.46     911  800.28   926.5  805.77  1068.5  881.89  1098.9  895.89
  1311.7  956.93  1382.6  980.17  1423.1  986.16  1483.8  991.21  1514.2  988.17
    1575  974.77  1605.3  970.92  1757.2  971.56  1777.5  974.06  1838.2  987.75
#Mann= 3 , 0 , 0
      10     .06       0     881    .045       0     911     .06       0
#XS Ineff= 2 , 0
          870.96  818.47
Permanent Ineff=
       F       F
Bank Sta=881,911
XS Rating Curve= 0 ,0
Exp/Cntr=0.3,0.1

Type RM Length L Ch R = 1 ,122489.7,36.7,37.8,38.6
XS GIS Cut Line= 4
      1599038.13      429436.073     1599676.407      429177.377
     1599939.208      428765.817     1600652.176      428369.767
#Sta/Elev= 30
    10.1 1021.41   141.8  977.91   232.9  952.07   435.5  913.16   536.8  888.94
   638.1  849.75   768.4  805.18   798.3  801.15   932.8  797.76   947.8  797.14
   957.8  798.46   997.6  820.49  1027.5  832.96  1147.1  896.93    1177  906.08
  1348.2  945.97  1368.3  946.78  1398.5  942.64  1539.5  914.48  1589.8  908.55
  1620.1  907.93  1650.3  910.29  1690.5  921.47  1720.7  924.69  1740.9  924.48
  1801.3  916.47  1831.5  918.76  1881.8  932.85  1952.3  960.72  1992.6  969.88
#Mann= 3 , 0 , 0
    10.1     .06       0   932.8    .045       0   957.8     .06       0
Bank Sta=932.8,957.8
XS Rating Curve= 0 ,0
Exp/Cntr=0.3,0.1

Type RM Length L Ch R = 1 ,122451.9,52.9,52.6,55.2
XS GIS Cut Line= 4
     1599047.801      429455.415     1599678.825      429196.719
     1600011.991      428764.074     1600701.661       428593.38
#Sta/Elev= 30
      10 1018.73    20.1 1018.03   130.4  981.96   210.6  960.11   300.9   941.1
   451.3  914.98   531.6  895.43     682  839.43   742.7  814.04     773  804.76
   803.3  800.36     940   797.7  955.09  797.08  962.35  799.05  1035.9  829.33
  1126.9  874.86  1177.5  895.38  1228.1  912.64  1339.7  936.41  1390.4  934.73
  1441.2  926.02  1583.3  875.64  1603.6   870.8  1644.2  879.96  1664.5  880.08
  1694.9  877.59  1745.7  866.26    1766  864.63  1816.7  884.85  1938.5  896.55
#Mann= 3 , 0 , 0
      10     .06       0     940    .045       0  962.35     .06       0
Bank Sta=940,962.35
XS Rating Curve= 0 ,0
Exp/Cntr=0.3,0.1

Type RM Length L Ch R = 1 ,122399.3,66.5,67.2,68
XS GIS Cut Line= 4
     1599067.143      429469.921      1599705.42      429208.808
     1600006.175      428875.626     1600716.735        428682.6
#Sta/Elev= 30
    10.1 1015.71    30.4 1011.64   131.8  979.72   202.8  962.21   294.1  943.68
   436.1  920.73   517.2  901.36   557.8   887.6   638.9  854.43   789.4  801.54
   849.2  798.76   953.9  797.74   968.9  796.94   978.9   797.9   988.9  801.15
  1018.8  817.55  1138.5  867.96  1289.8  909.68  1309.9  913.43  1350.3  913.62
  1461.2  892.08  1491.5  879.84  1541.9  846.31  1562.1  840.62  1582.3  841.61
  1602.4  845.87  1673.1  849.29  1733.6  847.97  1794.1  862.39  1874.8  873.58
#Mann= 3 , 0 , 0
    10.1     .06       0   953.9    .045       0   978.9     .06       0
Bank Sta=953.9,978.9
XS Rating Curve= 0 ,0
Exp/Cntr=0.3,0.1

Type RM Length L Ch R = 1 ,122332.1,128.3,132.1,133.3
XS GIS Cut Line= 5
     1599074.396      429486.845     1599719.926      429242.656
     1600084.504      428903.601     1600327.885      428892.411
     1600764.293      428917.588
#Sta/Elev= 30
    10.1 1011.22    30.4 1012.11   131.9  982.01   223.3  961.29   294.3  947.95
   426.3  929.41   537.9  903.07   639.4   862.1   781.6  808.96   812.1  799.77
   862.9  797.57  1000.3  797.42  1015.3  796.36  1020.3  797.66  1025.5     799
    1056  817.62    1188  870.41  1289.6  889.74  1330.2  881.64  1401.2  854.36
  1451.6  841.46  1491.3  828.52    1531  822.89  1560.8  821.32  1640.3  822.72
    1690  813.12  1769.5  813.22  1789.3   815.3  1819.1  823.78  1868.8  829.63
#Mann= 3 , 0 , 0
    10.1     .06       0  1000.3    .045       0  1020.3     .06       0
Bank Sta=1000.3,1020.3
XS Rating Curve= 0 ,0
Exp/Cntr=0.3,0.1

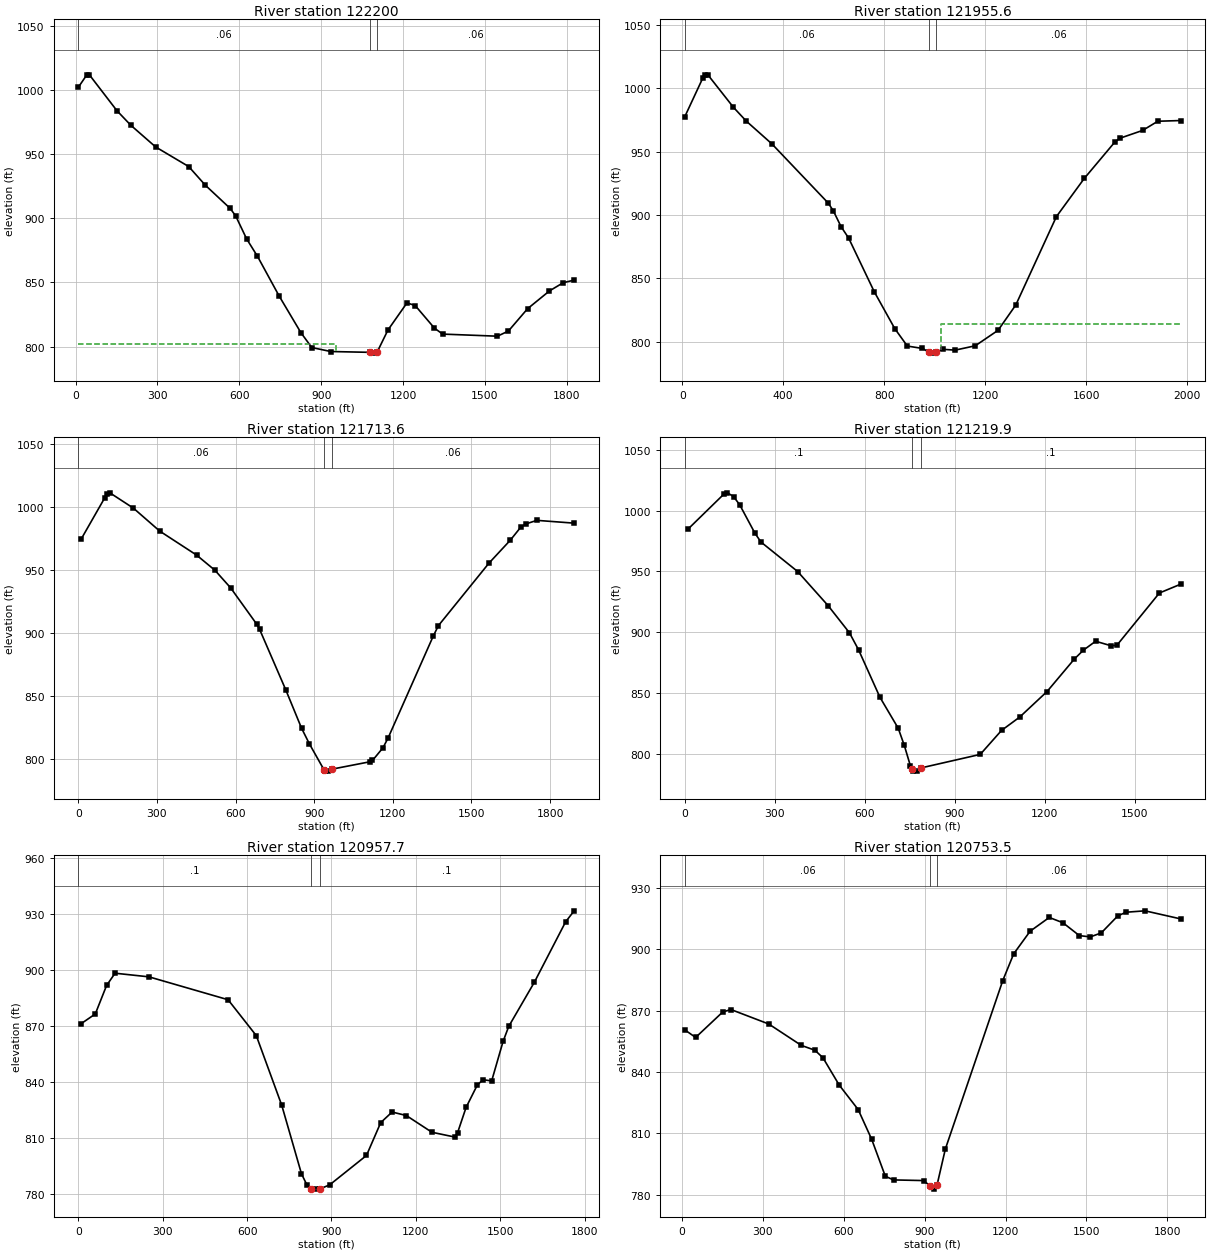
Type RM Length L Ch R = 1 ,122200  ,241.5,244.4,246.9
XS GIS Cut Line= 5
      1599066.22       429505.06     1599654.869      429320.138
     1599831.308      429253.041      1600166.79      429019.446
      1600778.28       428981.93
#Sta/Elev= 30
    10.1 1001.94    40.5 1011.41    50.6 1011.64   151.7  983.69   202.3  972.41
   293.3  955.52   414.7  940.21   475.4  925.74   566.4  907.68   586.7  901.83
   626.9  883.91   666.7  870.34   746.2  839.39   825.7  810.94   865.6  799.34
   935.4  796.24  1079.9   795.6  1094.9  794.99  1104.9  795.67  1144.8  812.99
  1214.6  834.12  1244.7  832.01    1315  814.48  1345.1  809.81    1546  808.17
  1586.2  812.18  1656.5  829.57  1736.8  843.43    1787  849.81  1827.2  851.83
#Mann= 3 , 0 , 0
    10.1     .06       0  1079.9    .045       0  1104.9     .06       0
#XS Ineff= 2 , 0
          954.55  802.22
Permanent Ineff=
       F       F
Bank Sta=1079.9,1104.9
XS Rating Curve= 0 ,0
Exp/Cntr=0.3,0.1

Type RM Length L Ch R = 1 ,121955.6,240.6,242.1,243.5
XS GIS Cut Line= 4
     1599100.439      429600.175     1599871.069      429260.496
     1600194.126       429198.37     1600964.793      429426.608
#Sta/Elev= 30
    10.1  977.51    81.2 1007.93    91.3 1010.55   101.5 1010.55   202.9  984.91
   253.7  974.05   355.1   956.1   578.4  909.39   598.7  903.25   629.1  890.85
   659.5  881.72     761  839.37   842.2  810.33     892  796.57   951.8   794.7
   976.7  791.97   991.7     791  1006.7  791.86  1031.6  794.01  1081.4  793.37
  1161.2   796.8  1251.5  809.01  1321.9  829.04  1482.6  898.68  1593.1  928.82
  1713.7  957.41  1733.8  960.49  1824.2  966.68  1884.5  973.93  1974.9  974.49
#Mann= 3 , 0 , 0
    10.1     .06       0   976.7    .045       0  1006.7     .06       0
#XS Ineff= 2 , 0
                          1024.1          814.22
Permanent Ineff=
       F       F
Bank Sta=976.7,1006.7
XS Rating Curve= 0 ,0
Exp/Cntr=0.3,0.1

Type RM Length L Ch R = 1 ,121713.6,489.1,493.7,498.3
XS GIS Cut Line= 4
     1599117.687      429632.571     1599778.009      429510.555
     1600402.444      429417.249       1600989.8      429464.188
#Sta/Elev= 30
      10  974.18   100.2 1007.08   110.2 1009.97   120.3 1011.27   210.5  999.03
   310.7  980.83     451  961.81   521.2  949.72   581.3   935.7   681.5  906.62
   691.5  902.86   791.8  854.54   851.9  824.11     882  811.59   937.1  791.23
   942.1  790.08   952.1  790.02   967.1  791.56  1112.5  797.45  1122.5  798.49
  1162.6   808.6  1182.6  816.61  1353.7  897.06    1374  905.67    1567  955.37
  1648.3  973.58  1688.9   984.1  1709.2  986.66  1749.9  989.38  1892.1  987.16
#Mann= 3 , 0 , 0
       0     .06       0   937.1    .045       0   967.1     .06       0
Bank Sta=937.1,967.1
XS Rating Curve= 0 ,0
Exp/Cntr=0.3,0.1

Type RM Length L Ch R = 1 ,121219.9,263.2,262.2,261.2
XS GIS Cut Line= 3
     1599314.639      429712.976     1600029.205       429947.09
     1600886.493      430222.573
#Sta/Elev= 30
    10.2  984.59   132.1 1013.95   142.3 1014.56   162.6 1011.44   182.9 1004.74
   233.7  981.35     254  974.05     376  949.85   477.6  921.77   548.7  899.44
   579.2  885.38   650.3  846.42   711.3  820.91   731.6  806.76   751.9  789.97
   757.2   787.8   762.1   785.8   772.2  785.66   787.2  788.29   984.6  799.42
  1055.5  819.12  1116.2  830.14  1207.2  851.12  1298.3  877.88  1328.6   885.2
  1369.1  892.48  1419.7  888.85  1439.9  889.15  1581.6  932.16  1652.4   939.4
#Mann= 3 , 0 , 0
       0      .1       0   757.2    .045       0   787.2      .1       0
Bank Sta=757.2,787.2
XS Rating Curve= 0 ,0
Exp/Cntr=0.3,0.1

Type RM Length L Ch R = 1 ,120957.7,201.8,204.2,206.6
XS GIS Cut Line= 4
     1599118.251      430029.598     1599828.847      430164.097
     1600054.104      430212.975      1600860.33      430282.532
#Sta/Elev= 30
      10  871.28    60.3  876.46   100.4  891.69   130.6  898.26   251.1  896.32
   532.4  884.08   632.8  864.86   723.2  827.67   793.4  790.99   813.4  784.83
   828.5  783.05   843.5   782.8   858.5  782.91   893.6  785.08  1024.5   800.8
  1075.1  818.36  1115.6  824.03  1166.1  822.16  1257.2  813.21  1338.1  810.66
  1348.2  812.87  1378.6  826.48    1419  838.61  1439.2   841.3  1469.6  840.66
  1510.1  861.75  1530.3  869.82  1621.3  893.41  1732.6  925.75  1762.9  931.62
#Mann= 3 , 0 , 0
       0      .1       0   828.5    .045       0   858.5      .1       0
Bank Sta=828.5,858.5
XS Rating Curve= 0 ,0
Exp/Cntr=0.3,0.1

Type RM Length L Ch R = 1 ,120753.5,247.9,246.1,244.2
XS GIS Cut Line= 4
     1599065.505      430065.064     1599752.916      430290.648
     1600034.944      430428.046      1600812.21      430662.913
#Sta/Elev= 30
      10  860.58    50.2  856.87   150.7  869.31   180.9  870.52   321.5  863.44
   442.1     853   492.4  850.65   522.5  846.95   582.8  833.61   653.1  821.65
   703.4  807.07   753.8  789.08   784.2  787.29   895.5  786.97     921  784.26
     936  782.79   946.1  785.05   976.5  802.39  1189.4  884.63    1230  897.72
  1290.9  908.76    1362  915.48  1412.7  912.89  1473.6  906.61  1514.2  905.99
  1554.8  907.93  1615.7  916.19  1646.2  918.03  1717.2  918.72  1849.2  914.78
#Mann= 3 , 0 , 0
      10     .06       0     921    .045       0   946.1     .06       0
Bank Sta=921,946.1
XS Rating Curve= 0 ,0
Exp/Cntr=0.3,0.1

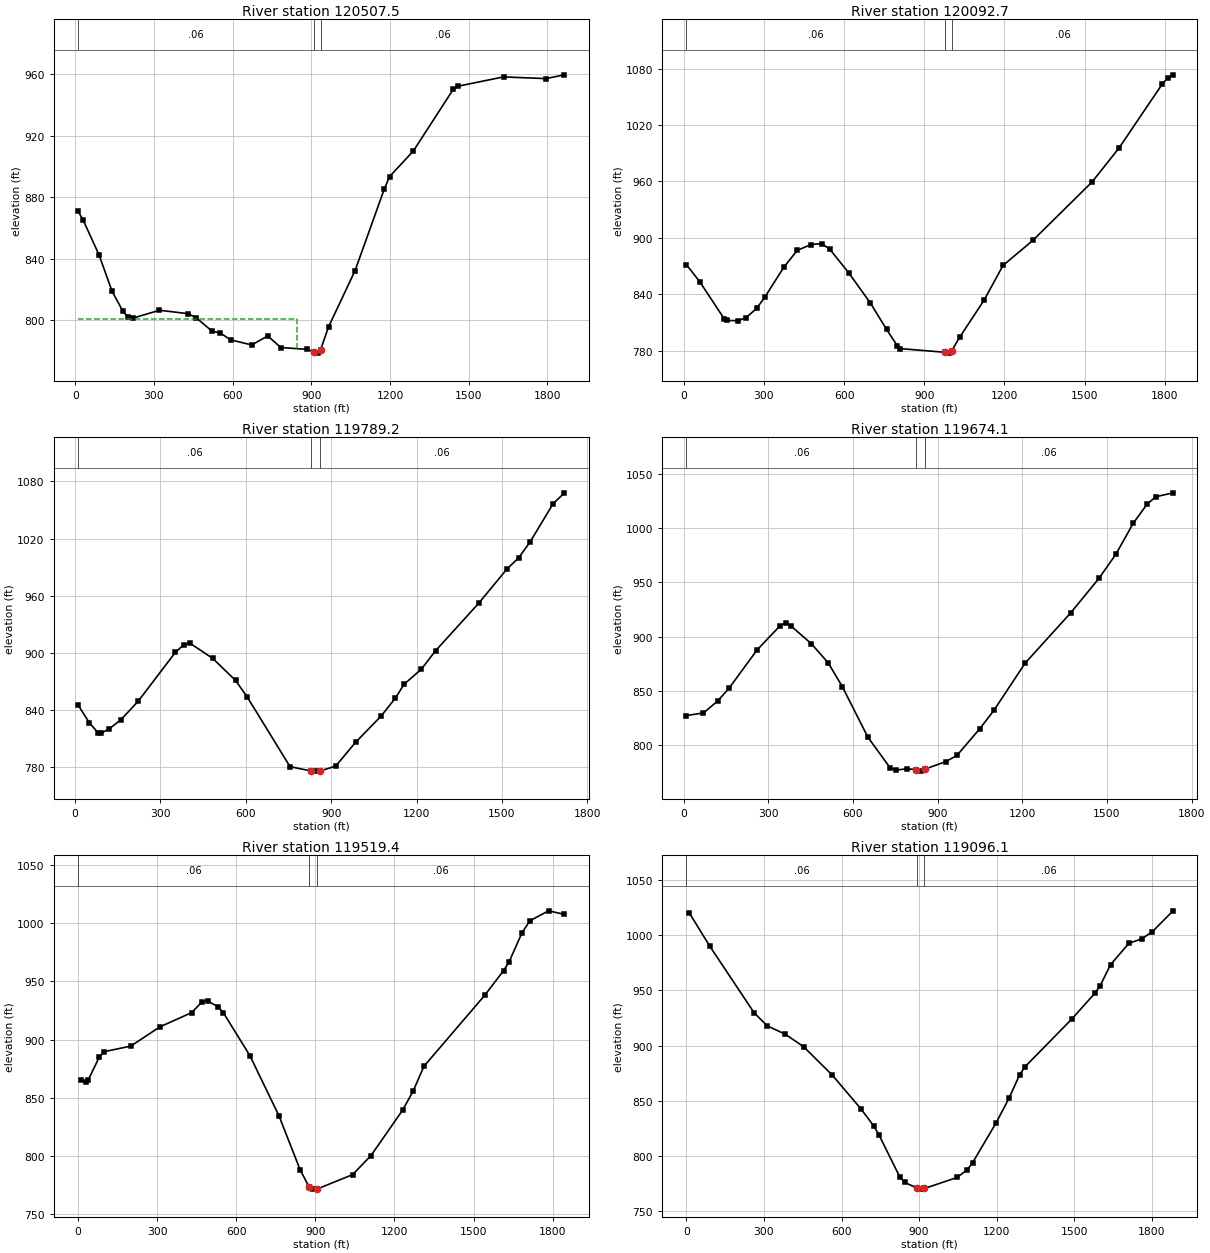
Type RM Length L Ch R = 1 ,120507.5,414.3,414.8,415.3
XS GIS Cut Line= 3
     1598926.778      430566.397     1599547.478      430520.263
     1600747.131       430845.08
#Sta/Elev= 30
      10  871.13    30.1  865.08    90.4  842.59   140.5  818.77   180.7  806.18
   200.8  801.88   220.9  801.39   321.2  806.46   431.7  804.21   461.8  801.45
     522  792.82   552.1  791.74   592.3  787.23   672.9  783.87   733.6  789.74
   784.1  782.22   885.1  781.01   910.5  779.18   925.5  778.57   935.6  780.92
     966  795.72    1067  832.31  1178.2  885.26  1198.4  893.41  1289.3  910.11
  1440.9  950.07  1461.1  952.25  1632.9  958.24  1794.5  957.12  1865.3  959.59
#Mann= 3 , 0 , 0
      10     .06       0   910.5    .045       0   935.6     .06       0
#XS Ineff= 2 , 0
          847.06  800.86
Permanent Ineff=
       F       F
Bank Sta=910.5,935.6
XS Rating Curve= 0 ,0
Exp/Cntr=0.3,0.1

Type RM Length L Ch R = 1 ,120092.7,302.4,303.4,303
XS GIS Cut Line= 4
     1598895.438      430692.663     1599401.057      430870.718
     1599989.316       431062.33     1600635.283      431263.298
#Sta/Elev= 30
    10.1  871.42    60.7  852.97   151.7  813.69   161.8  812.13   202.3  811.75
   232.6  814.87   273.1  824.97   303.4  836.82   374.2  868.57   424.8  886.69
   475.4  892.72   515.8  893.94   546.2  887.98   617.2  862.84   698.3  830.67
   759.2  802.47   799.8  784.94   809.9  782.11   977.5  778.19   992.5  777.29
  1002.6  779.73    1033  794.35  1124.3  833.82  1195.1   870.7  1306.2  897.18
  1528.3  959.52  1629.3  995.73  1790.9 1063.68    1811 1070.12  1831.2 1073.47
#Mann= 3 , 0 , 0
    10.1     .06       0   977.5    .045       0  1002.6     .06       0
Bank Sta=977.5,1002.6
XS Rating Curve= 0 ,0
Exp/Cntr=0.3,0.1

Type RM Length L Ch R = 1 ,119789.2,110.8,115.1,120.9
XS GIS Cut Line= 4
     1598939.905      430812.225     1599622.496      431159.103
     1599923.755      431267.247     1600533.385      431441.397
#Sta/Elev= 30
    10.1  845.78    50.4  826.78    80.6  816.48    90.7  815.73   120.9  820.57
   161.2  829.95   221.6  849.22   352.6  900.61   382.8  908.76     403  910.39
   483.6  894.37   564.2  871.17   604.5  854.12   755.6  780.75   830.7   776.2
   845.6  776.08   860.7  776.23   915.7  781.32   985.7  806.22  1075.8  833.92
    1126  852.77  1156.2  867.12  1216.6  882.91  1266.9  902.33  1417.9  951.94
  1518.5  988.31  1558.8  999.75    1599 1016.38  1679.5 1056.35  1719.8  1067.9
#Mann= 3 , 0 , 0
    10.1     .06       0   830.7    .045       0   860.7     .06       0
Bank Sta=830.7,860.7
XS Rating Curve= 0 ,0
Exp/Cntr=0.3,0.1

Type RM Length L Ch R = 1 ,119674.1,162.3,154.7,147.1
XS GIS Cut Line= 4
     1598944.658      430931.314     1599560.868      431146.106
     1599759.461      431391.427     1600503.043      431574.917
#Sta/Elev= 30
      10  827.18    70.3   829.6   120.5   840.6   160.6  852.31     261  887.96
   341.3  909.89   361.4  912.85   381.5  909.59   451.8  893.63     512  875.92
   562.2  853.91   652.6  807.35   731.5  779.07   751.2  776.88   790.7  778.08
     825  777.37  840.15  775.95     855   777.8   928.7  784.71   968.2  790.37
  1048.8  814.91  1099.2  831.93  1210.1  875.59  1371.3  921.88  1472.1  953.91
  1532.5  976.39    1593 1004.54  1643.4 1022.61  1673.6 1029.01  1734.1 1032.61
#Mann= 3 , 0 , 0
      10     .06       0     825    .045       0     855     .06       0
Bank Sta=825,855
XS Rating Curve= 0 ,0
Exp/Cntr=0.3,0.1

Type RM Length L Ch R = 1 ,119519.4,426.4,423.3,419.1
XS GIS Cut Line= 4
      1598751.68      431107.663     1599455.129      431375.391
     1599823.335      431462.936     1600512.546      431648.372
#Sta/Elev= 30
      10   865.1    30.1  863.87    40.1  865.79    80.3  884.71   100.4  889.74
   200.7  894.51   311.1  911.03   431.5  923.24   471.7  932.74   491.7  933.22
   531.9  928.16     552  922.98   652.3  886.29   762.6  834.54   842.3  788.54
   877.1   773.4   892.1  771.72   907.1  771.83  1041.5  784.16  1111.2  800.48
  1231.7   839.7  1271.9  856.23  1312.1  877.16  1543.3   938.3  1613.7  959.24
  1633.8  966.26    1684  991.86  1714.2 1002.16  1784.6 1010.61  1844.9 1007.54
#Mann= 3 , 0 , 0
       0     .06       0   877.1    .045       0   907.1     .06       0
Bank Sta=877.1,907.1
XS Rating Curve= 0 ,0
Exp/Cntr=0.3,0.1

Type RM Length L Ch R = 1 ,119096.1,799.5,798.5,798.5
XS GIS Cut Line= 3
     1598745.796      431875.311     1599649.738      431813.636
     1600612.144      431646.939
#Sta/Elev= 30
    10.1 1020.72    90.6  990.07   261.7  929.77   312.1  917.93   382.6  910.22
     453  898.98   563.8  873.26   674.5   842.7   724.8  826.91     745  818.84
   825.5  780.66   845.6  775.68     891  770.61     906  769.64     921  770.25
    1047   780.2  1087.3  787.38  1107.4  793.71  1198.1  829.82  1248.4  852.31
  1288.7  873.21  1308.8  880.43  1490.1  923.82  1580.7  947.54  1600.8  954.36
  1641.1  973.45  1711.6  992.68  1761.9  996.93  1802.2 1003.22  1882.8 1022.27
#Mann= 3 , 0 , 0
       0     .06       0     891    .045       0     921     .06       0
Bank Sta=891,921
XS Rating Curve= 0 ,0
Exp/Cntr=0.3,0.1

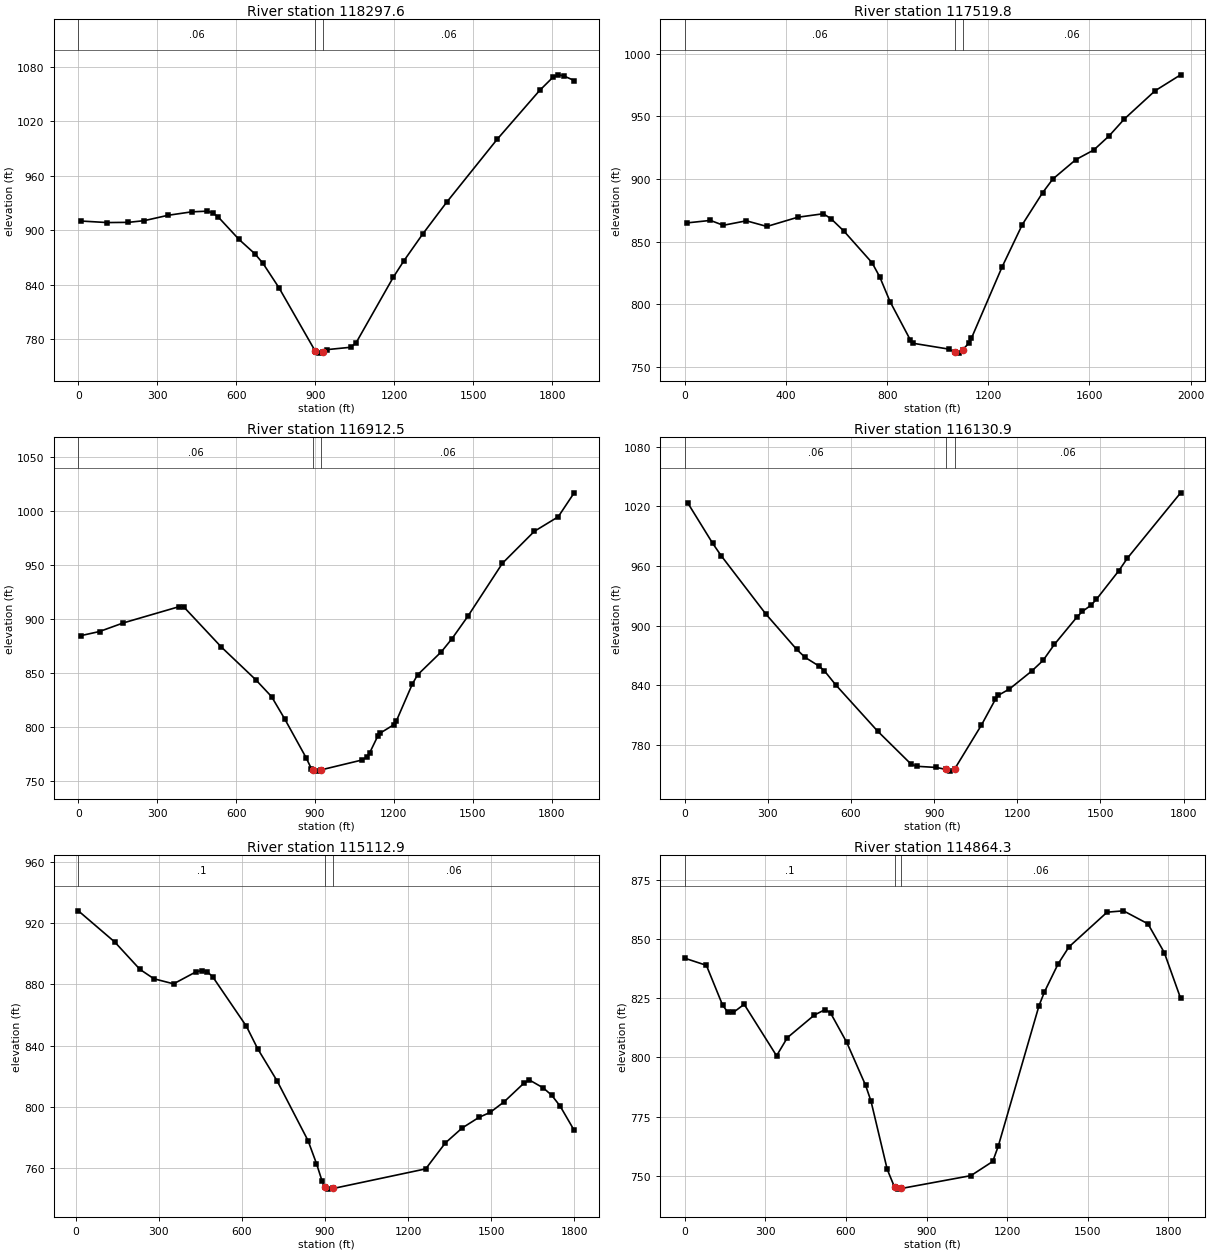
Type RM Length L Ch R = 1 ,118297.6,783.8,777.8,771.8
XS GIS Cut Line= 3
     1598781.653      432549.187     1599364.881       432368.62
     1600637.019      432405.976
#Sta/Elev= 30
      10  910.09   110.1   908.4   190.2  908.64   250.2  910.49   340.3  916.38
   430.4  920.19   490.4  920.95   510.5  918.92   530.5  914.79   610.5  889.79
   671.1  873.91   701.4   863.5   762.1  836.69   898.6  767.64   903.5  765.89
   913.6  764.81   928.6  766.59   943.9  768.65  1034.8  771.27    1055  776.21
  1196.4  848.34  1236.8  866.47  1307.5   895.6  1398.4  930.54  1590.3  999.82
  1751.9 1053.65  1802.4 1068.15  1822.6 1070.88  1842.8  1069.8  1883.2 1064.63
#Mann= 3 , 0 , 0
       0     .06       0   898.6    .045       0   928.6     .06       0
Bank Sta=898.6,928.6
XS Rating Curve= 0 ,0
Exp/Cntr=0.3,0.1

Type RM Length L Ch R = 1 ,117519.8,598.1,607.3,616.9
XS GIS Cut Line= 4
     1598850.756      433099.328     1599679.046      433175.451
     1600216.818      432860.013      1600659.18      432616.129
#Sta/Elev= 30
    10.1  865.11   101.4  867.06   152.2  863.17   243.4  866.75   324.6  862.24
   446.3  869.58   547.8  872.39   578.2   868.4   628.9  858.57   740.5  833.25
   770.9  821.94   811.5  802.28   892.1  771.52   902.2  769.01    1043  764.38
  1068.2  761.84  1083.2  761.14  1098.2  763.71  1123.4  769.18  1133.5  773.13
  1254.1  829.74  1334.6  863.78    1415  889.26  1455.2   900.1  1546.2  915.59
  1616.9  923.25  1677.5  934.49  1738.1  948.05  1859.3  970.52  1960.4  983.26
#Mann= 3 , 0 , 0
       0     .06       0  1068.2    .045       0  1098.2     .06       0
Bank Sta=1068.2,1098.2
XS Rating Curve= 0 ,0
Exp/Cntr=0.3,0.1

Type RM Length L Ch R = 1 ,116912.5,782.5,781.6,780.3
XS GIS Cut Line= 3
     1598921.434      433163.304     1599756.548      433487.851
     1600660.123      433891.293
#Sta/Elev= 30
    10.1  884.23    80.5  888.03   171.1     896   382.5  910.98   402.7  910.34
   543.6  873.72   674.5  843.44   734.9  827.74   785.2  806.95   865.8  771.39
   885.9  761.21   891.1  760.04   906.1  758.82   921.1  759.86  1077.7  769.05
  1097.9  771.79    1108  775.81  1138.3  791.05  1148.4  794.09  1198.9  801.65
    1209  805.03  1269.6  839.12  1289.8  847.85  1380.6   869.3    1421  881.42
  1481.6  902.25  1612.9  951.25  1734.1  980.77  1824.9  994.22  1885.5 1016.39
#Mann= 3 , 0 , 0
       0     .06       0   891.1    .045       0   921.1     .06       0
Bank Sta=891.1,921.1
XS Rating Curve= 0 ,0
Exp/Cntr=0.3,0.1

Type RM Length L Ch R = 1 ,116130.9,1015.8,1018,1020.4
XS GIS Cut Line= 3
     1598697.381      433926.119       1599422.3      434141.441
     1600412.783      434435.715
#Sta/Elev= 30
    10.1 1023.67   100.8  982.75   131.1  970.47   292.4  911.83   403.3  876.41
   433.6  868.35     484  859.57   504.1  854.63   544.5  840.69   695.7  794.18
     817  760.86   837.3  758.79   908.2  757.61   943.8  755.58   958.8  753.93
   973.8  756.02  1070.3  800.05  1120.9  826.02    1131  830.06  1171.6  836.44
  1252.6  854.59  1293.1  865.18  1333.6  881.18  1414.7  908.54  1434.9   914.4
  1465.3  920.48  1485.6  926.58  1566.6  955.35    1597  967.78  1789.5 1033.59
#Mann= 3 , 0 , 0
       0     .06       0   943.8    .045       0   973.8     .06       0
Bank Sta=943.8,973.8
XS Rating Curve= 0 ,0
Exp/Cntr=0.3,0.1

Type RM Length L Ch R = 1 ,115112.9,249.2,248.6,247.6
XS GIS Cut Line= 3
     1598341.085      434640.191     1599151.643      435031.247
     1599927.294      435487.126
#Sta/Elev= 30
    10.1  927.93   141.6  907.58   232.6  889.72   283.1  883.61   353.9  880.32
   434.8  888.14     455     889   475.3  888.24   495.5  884.81   616.8  852.62
   657.3  838.03   728.1  816.84   839.3  778.02   869.6  763.12   889.8  751.75
     900  747.82   910.1  746.44   930.3  746.87  1263.9  759.65  1334.6  776.52
  1395.3  786.29    1456  793.22  1496.4  796.46  1546.9  803.38  1617.7  815.43
  1637.9  817.64  1688.5  812.41  1718.8  807.64  1749.1  800.58  1799.7  784.81
#Mann= 3 , 0 , 0
    10.1      .1       0     900    .045       0   930.3     .06       0
Bank Sta=900,930.3
XS Rating Curve= 0 ,0
Exp/Cntr=0.3,0.1

Type RM Length L Ch R = 1 ,114864.3,419.9,403.2,386.6
XS GIS Cut Line= 4
     1598227.735      434949.509     1598891.686      435148.694
     1599173.074      435281.485     1599925.551      435657.723
#Sta/Elev= 30
       0  841.89    80.4  838.89   140.6  822.12   160.7  818.99   180.8  819.02
     221  822.44   341.6  800.71   381.8  808.36   482.2   817.9   522.4  820.21
   542.5  818.79   602.8  806.36   673.1  788.21   693.2  781.51   753.4  752.79
   781.1  745.14   793.6  744.42   806.1   744.7  1065.1  750.12  1146.2   756.1
  1166.5  762.44  1318.6   821.9  1338.8  827.69  1389.5  839.49    1430  846.68
    1572  861.33  1632.8   861.9    1724  856.41  1784.8  844.27  1845.6  824.95
#Mann= 3 , 0 , 0
       0      .1       0   781.1    .045       0   806.1     .06       0
Bank Sta=781.1,806.1
XS Rating Curve= 0 ,0
Exp/Cntr=0.3,0.1

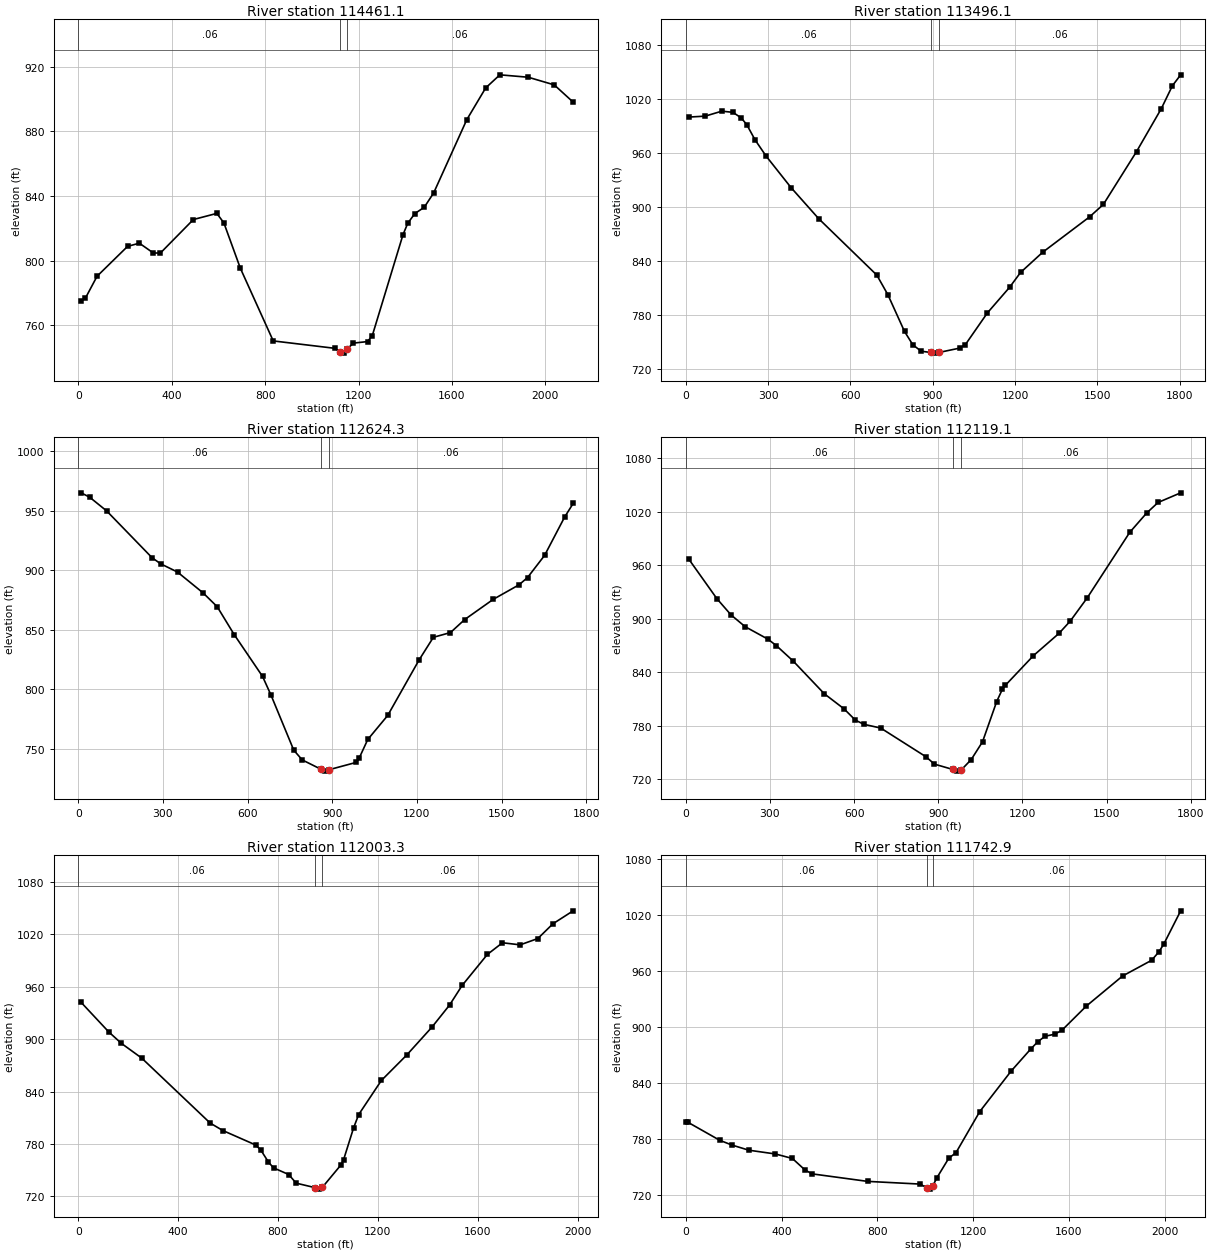
Type RM Length L Ch R = 1 ,114461.1,954.7,965.1,975.3
XS GIS Cut Line= 4
     1598108.833      435218.053     1598814.961      435624.192
     1599149.867      435417.081     1599850.311      435998.958
#Sta/Elev= 30
    10.1  775.09    30.2   776.8    80.5  790.45   211.2  808.92   261.5  810.88
   321.8  804.78     352  804.84   492.8  825.51   593.3  829.31   623.5  823.42
   693.9  795.42   834.8  750.43  1097.3  745.88  1122.7  743.57  1137.7  742.88
  1152.7  745.63  1178.1  749.08  1238.7  750.02    1259  753.71  1390.5  816.15
  1410.7  823.17  1441.1   829.2  1481.5  833.09    1522  842.03  1663.7   887.3
  1744.6  906.93  1805.3  915.02  1926.7  913.53    2038  908.81    2119  898.15
#Mann= 3 , 0 , 0
       0     .06       0  1122.7    .045       0  1152.7     .06       0
Bank Sta=1122.7,1152.7
XS Rating Curve= 0 ,0
Exp/Cntr=0.3,0.1

Type RM Length L Ch R = 1 ,113496.1,875.6,871.8,868.1
XS GIS Cut Line= 3
     1597949.697      435762.486     1598716.355      436249.472
      1599479.72      436718.133
#Sta/Elev= 30
    10.1  999.79    70.6 1000.83   131.2 1006.37   171.6 1005.06   201.8  998.93
     222  991.44   252.3  974.51   292.7  956.43   383.5  921.45   484.4  886.87
   696.3  824.16   736.7   802.3   797.2  761.55   827.5  746.74   857.8  739.59
   893.3  738.15   908.3  737.45   923.3  738.23   998.8  743.05    1019  746.85
  1099.5   782.2    1180   810.5  1220.3  827.09  1300.8  849.53  1471.9  888.89
  1522.2  902.72    1643   961.4  1733.5 1009.23  1773.8 1034.61    1804 1046.75
#Mann= 3 , 0 , 0
       0     .06       0   893.3    .045       0   923.3     .06       0
Bank Sta=893.3,923.3
XS Rating Curve= 0 ,0
Exp/Cntr=0.3,0.1

Type RM Length L Ch R = 1 ,112624.3,504.2,505.2,505.7
XS GIS Cut Line= 3
     1597606.414      436883.213     1598460.732      437012.433
     1599336.171       437170.31
#Sta/Elev= 30
      10  964.95    40.2  961.29   100.5  949.77   261.2  910.53   291.4  905.42
   351.6  898.43   442.1  880.96   492.3  869.33   552.6  845.88     653  810.81
   683.2  794.98   763.6  748.85   793.7  740.69   859.1  732.97   874.1  731.28
   889.1   732.5   985.3  738.64   995.4  742.21  1025.8  757.84  1096.5  778.01
  1207.7  824.63  1258.3  843.65  1318.9  847.62  1369.5  858.58  1470.6  875.53
  1561.5  887.67  1591.9  893.77  1652.5  912.43  1723.3  944.53  1753.6     956
#Mann= 3 , 0 , 0
       0     .06       0   859.1    .045       0   889.1     .06       0
Bank Sta=859.1,889.1
XS Rating Curve= 0 ,0
Exp/Cntr=0.3,0.1

Type RM Length L Ch R = 1 ,112119.1,113.5,115.8,118.4
XS GIS Cut Line= 4
     1597575.357      437219.231      1598416.36      437465.842
     1598615.546      437497.458     1599301.628      437478.488
#Sta/Elev= 30
    10.1  967.18   110.8  922.55   161.2  904.32   211.5  891.11   292.1  877.21
   322.4  869.96   382.8  852.51   493.6  815.82   564.1  798.84   604.4   786.2
   634.6   781.5   695.1  777.25   856.3  745.01   886.5  736.74   952.2  730.77
   967.2   728.9   982.2  730.29  1017.6   741.9  1057.9  761.84  1108.4  807.04
  1128.6  820.81  1138.7  825.07  1239.6  858.65  1330.4  883.55  1370.8  897.44
  1431.4  923.57  1582.8  997.06  1643.3 1018.79  1683.7 1030.58  1764.4 1041.43
#Mann= 3 , 0 , 0
       0     .06       0   952.2    .045       0   982.2     .06       0
Bank Sta=952.2,982.2
XS Rating Curve= 0 ,0
Exp/Cntr=0.3,0.1

Type RM Length L Ch R = 1 ,112003.3,266.3,260.4,254.4
XS GIS Cut Line= 4
      1597562.71      437282.465     1598350.514      437519.013
     1598595.125       437655.48     1599472.358      437712.452
#Sta/Elev= 30
    10.2  942.56   121.9  908.41   172.6  895.27   253.9  878.44   528.1  804.04
   578.8   795.5   710.8  778.89   731.2  773.01   761.6  759.38   781.9  752.75
   842.6  745.14   872.6  735.25   947.6  730.14   962.6  728.41   977.6  730.54
  1052.6  756.35  1062.6  762.22  1102.7  798.72  1122.9  813.76  1213.8  852.81
  1314.8  881.77  1415.9  913.73  1486.6  939.02  1537.1  961.55  1638.2  997.07
  1698.8 1010.45  1769.5 1008.05  1840.3 1015.28  1900.9 1032.18  1981.7    1047
#Mann= 3 , 0 , 0
       0     .06       0   947.6    .045       0   977.6     .06       0
Bank Sta=947.6,977.6
XS Rating Curve= 0 ,0
Exp/Cntr=0.3,0.1

Type RM Length L Ch R = 1 ,111742.9,74.1,72.9,71.6
XS GIS Cut Line= 4
     1597468.475       438227.18     1598225.521      437818.616
      1598602.85      437835.721     1599429.005      437763.266
#Sta/Elev= 30
       0  797.75    10.1  797.75   141.7   778.6   192.3  773.53   263.1  767.98
   374.5  763.91   445.3  759.08   495.9  747.19   526.3  742.61   759.1  734.51
   979.5   731.6  1006.8  727.49  1019.3  726.19  1031.8  729.75  1049.1  738.49
  1098.8  759.47  1128.6  765.29    1228  809.44  1359.3  852.98  1440.2  876.36
  1470.6  884.44  1500.9   890.3  1541.4  892.47  1571.7  896.81  1672.9   922.6
  1824.6  954.94  1945.9  971.81  1976.3  980.84  1996.5  989.05  2067.3 1024.89
#Mann= 3 , 0 , 0
       0     .06       0  1006.8    .045       0  1031.8     .06       0
Bank Sta=1006.8,1031.8
XS Rating Curve= 0 ,0
Exp/Cntr=0.3,0.1