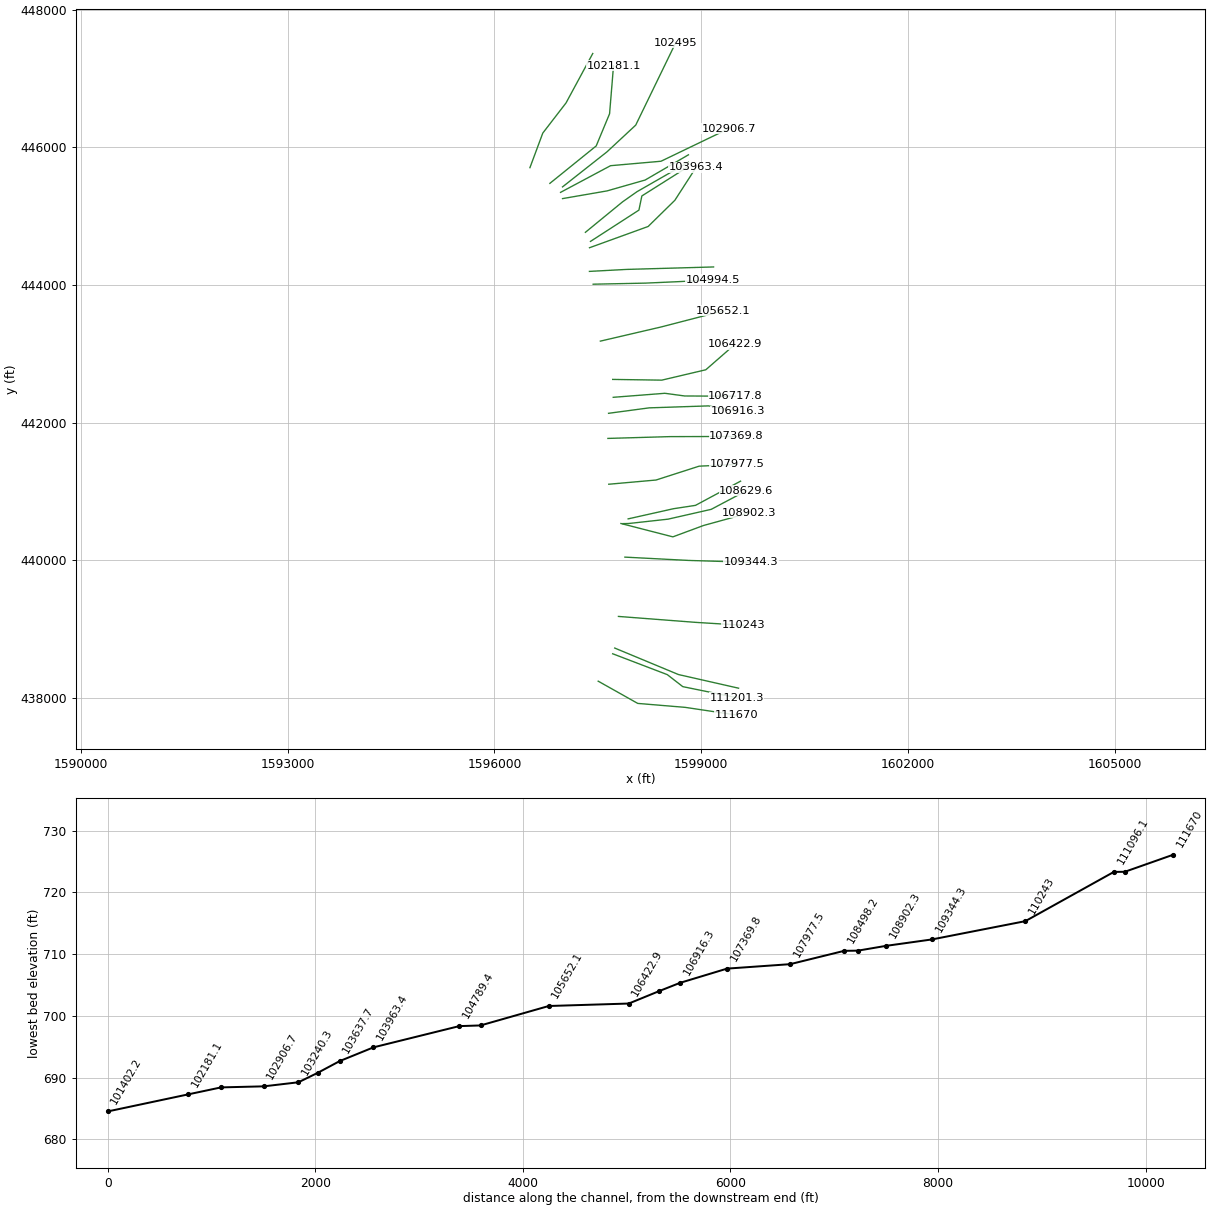
HEC-RAS study BEECHFK.prj: BEECHFK

--- BEECHFK.g01 (geometry) --- (continued)

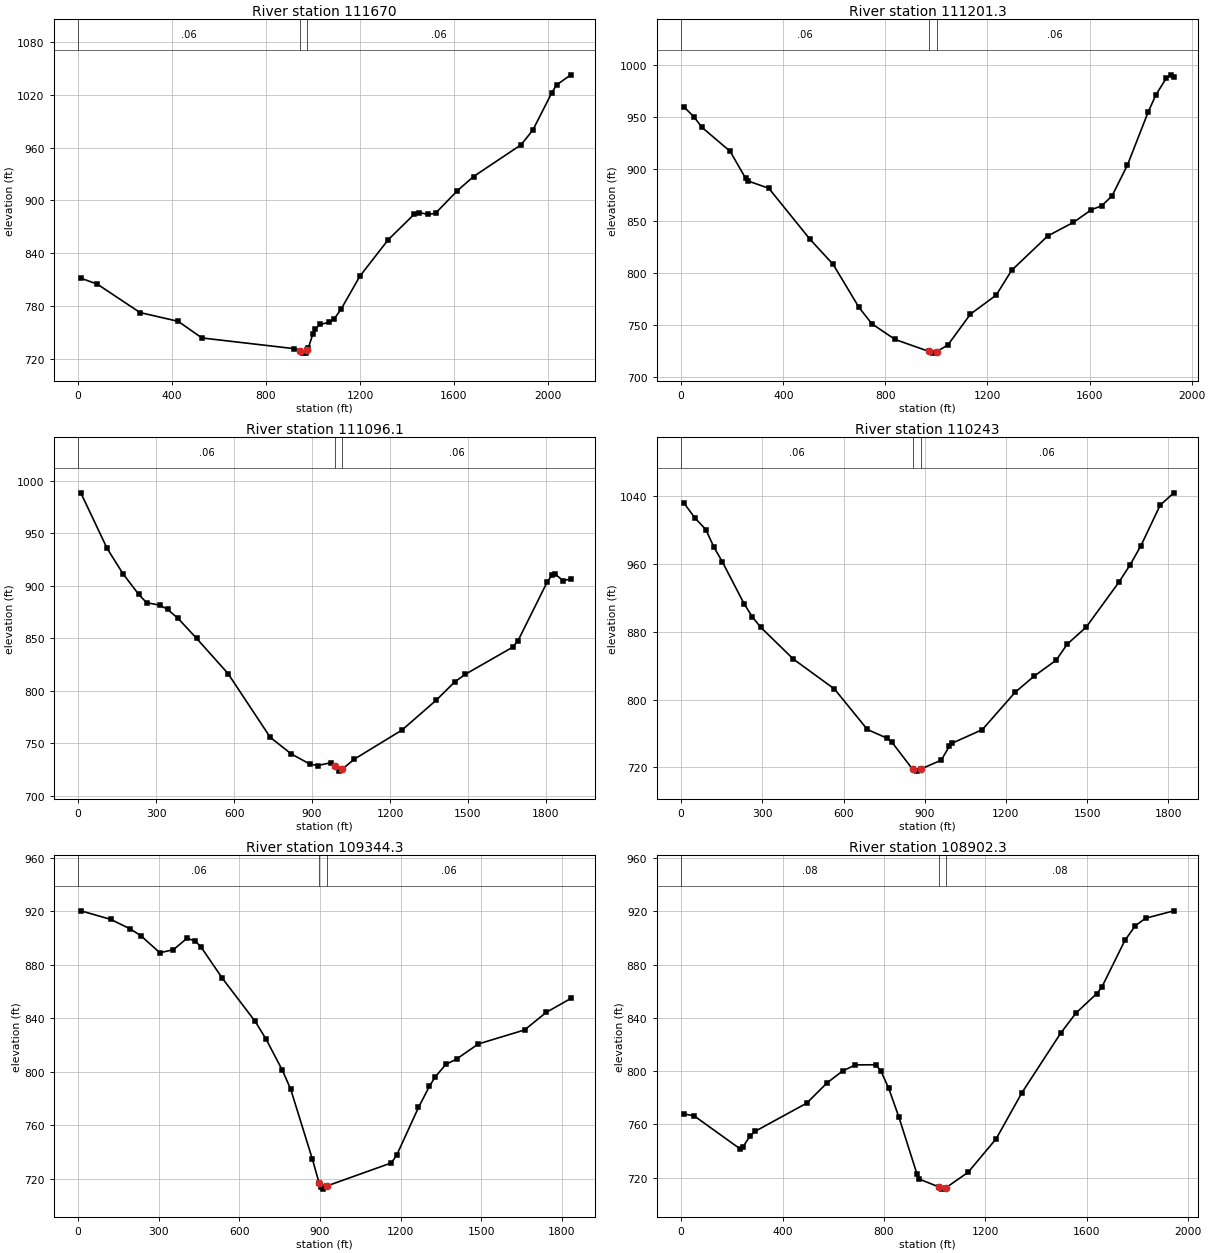
Type RM Length L Ch R = 1 ,111670  ,474.5,468.8,463
XS GIS Cut Line= 4
     1597505.931      438246.922     1598080.124      437923.938
     1598769.156      437866.519     1599508.747      437756.183
#Sta/Elev= 30
    10.1  811.52    81.1  804.75   263.5  772.31   425.7  762.36     527  743.41
   919.3  731.23   944.4  728.81   959.4  726.13   969.4  726.81   974.4  729.23
   979.5   731.7   999.5  747.86  1009.5   753.3  1029.6   758.8  1069.6  761.27
  1089.7  764.92  1119.7  776.21  1199.9  813.84  1320.2  855.22  1431.1  884.33
  1451.3  886.16  1491.7  884.04    1522  885.46    1613  910.62  1683.7  927.22
  1885.8  963.32  1936.3  980.15  2017.2 1022.75  2037.4 1031.53    2098 1043.02
#Mann= 3 , 0 , 0
       0     .06       0   944.4    .045       0   974.4     .06       0
Bank Sta=944.4,974.4
XS Rating Curve= 0 ,0
Exp/Cntr=0.3,0.1

Type RM Length L Ch R = 1 ,111201.3,102.5,105.2,109.6
XS GIS Cut Line= 4
     1597716.337      438645.004     1598508.579      438342.087
     1598733.825      438167.328     1599514.416      438008.103
#Sta/Elev= 30
    10.1  959.59    50.5  949.81    80.8  939.94   191.8  916.84   252.4  890.99
   262.5  888.36   343.3  881.39   504.9  832.43   595.7  808.33   696.7  767.11
   747.2  751.44   838.1  736.44   970.8  724.97   985.8  723.35  1000.8  724.77
  1044.8  731.17  1133.3  760.76  1234.1  778.97  1294.6  802.72  1435.8  835.66
  1536.6  848.74  1607.2  860.81  1647.6  864.67  1687.9  874.07  1748.4  903.79
  1829.1  954.31  1859.3  970.74  1899.7  986.73  1919.8  990.17  1929.9  988.29
#Mann= 3 , 0 , 0
       0     .06       0   970.8    .045       0  1000.8     .06       0
Bank Sta=970.8,1000.8
XS Rating Curve= 0 ,0
Exp/Cntr=0.3,0.1

Type RM Length L Ch R = 1 ,111096.1,849.9,853.1,854.5
XS GIS Cut Line= 3
     1597746.155      438727.755     1598671.357      438342.996
     1599542.914      438145.056
#Sta/Elev= 30
    10.1  988.76   111.3  935.75   172.1  911.72   232.8  891.94   263.2  884.01
   313.8   881.6   344.1   877.6   384.6  868.94   455.5  849.99   576.9  816.29
   738.9  755.64   819.8  739.75   890.7  730.17     921  728.65   971.7  731.29
     987  727.76    1002  723.33    1017  725.37    1063  734.81  1245.8  762.45
  1377.8  790.96  1448.9  808.41  1489.5  815.65  1672.3  841.58  1692.6  847.77
  1804.4  903.49  1824.7  910.84  1834.8   911.4  1865.3  905.04  1895.8   906.5
#Mann= 3 , 0 , 0
       0     .06       0     987    .045       0    1017     .06       0
Bank Sta=987,1017
XS Rating Curve= 0 ,0
Exp/Cntr=0.3,0.1

Type RM Length L Ch R = 1 ,110243  ,898.5,898.7,898.8
XS GIS Cut Line= 3
     1597800.205      439187.163     1598919.881      439101.034
      1599616.09       439057.97
#Sta/Elev= 30
    10.1 1032.36    50.6 1014.68    91.1 1000.95   121.4  979.89   151.8  963.02
   232.7  913.12     263  897.66   293.4  885.58   414.8  847.74   566.6  812.38
     688  764.61   758.8  754.57     779  749.49   855.1  717.62   870.1  715.35
   885.1  717.77   961.1  728.32   991.5  745.01  1001.6  748.43  1112.9   764.4
  1234.2  808.59    1305  827.79  1385.8  846.52  1426.3  865.32    1497  885.71
  1618.3  939.04  1658.8  959.08  1699.2  981.98    1770 1029.74  1820.5 1044.33
#Mann= 3 , 0 , 0
       0     .06       0   855.1    .045       0   885.1     .06       0
Bank Sta=855.1,885.1
XS Rating Curve= 0 ,0
Exp/Cntr=0.3,0.1

Type RM Length L Ch R = 1 ,109344.3,437.9,442,446.1
XS GIS Cut Line= 3
     1597893.511      440048.453     1598814.709      440000.556
     1599725.614       439972.71
#Sta/Elev= 30
    10.1  920.25   121.6  913.83   192.6  906.84   233.1  901.71   304.1  888.91
   354.8  891.27   405.5  899.84   435.9  897.54   456.2  893.55   537.2  869.72
   658.9  837.66   699.4  824.41   760.3  801.05   790.7  787.21   871.8  734.77
   897.3  716.63   902.2  713.82   912.3  712.39   927.3  714.86  1165.5  731.95
  1185.7  737.81  1266.7  773.37  1307.2  789.07  1327.5   795.8    1368  805.48
  1408.5  809.54  1489.5  820.82  1661.6  831.28  1742.6  844.46  1833.8  854.79
#Mann= 3 , 0 , 0
       0     .06       0   897.3    .045       0   927.3     .06       0
Bank Sta=897.3,927.3
XS Rating Curve= 0 ,0
Exp/Cntr=0.3,0.1

Type RM Length L Ch R = 1 ,108902.3,272.3,272.8,273.3
XS GIS Cut Line= 4
     1597836.007      440536.747      1598589.72      440342.727
      1599034.72      440507.808     1599700.248      440690.802
#Sta/Elev= 30
    10.1  767.79    50.5  766.46   232.5  741.58   242.6  742.74   272.9  751.54
   293.1  754.89   495.3  775.93   576.1  791.24   636.8  800.08   687.3  804.64
   768.2  804.75   788.4  799.81   818.7  787.01   859.1  765.25   929.8  722.85
   939.9  718.84  1015.7  713.05  1030.7  711.35  1045.7  712.57  1131.7  723.97
  1242.8  749.27  1344.3  783.85  1496.5  828.36  1557.4  843.64  1638.6  858.06
  1658.9  862.95  1750.3  898.17  1790.9  909.04  1831.5  914.76  1943.1  920.34
#Mann= 3 , 0 , 0
       0     .08       0  1015.7    .045       0  1045.7     .08       0
Bank Sta=1015.7,1045.7
XS Rating Curve= 0 ,0
Exp/Cntr=0.3,0.1

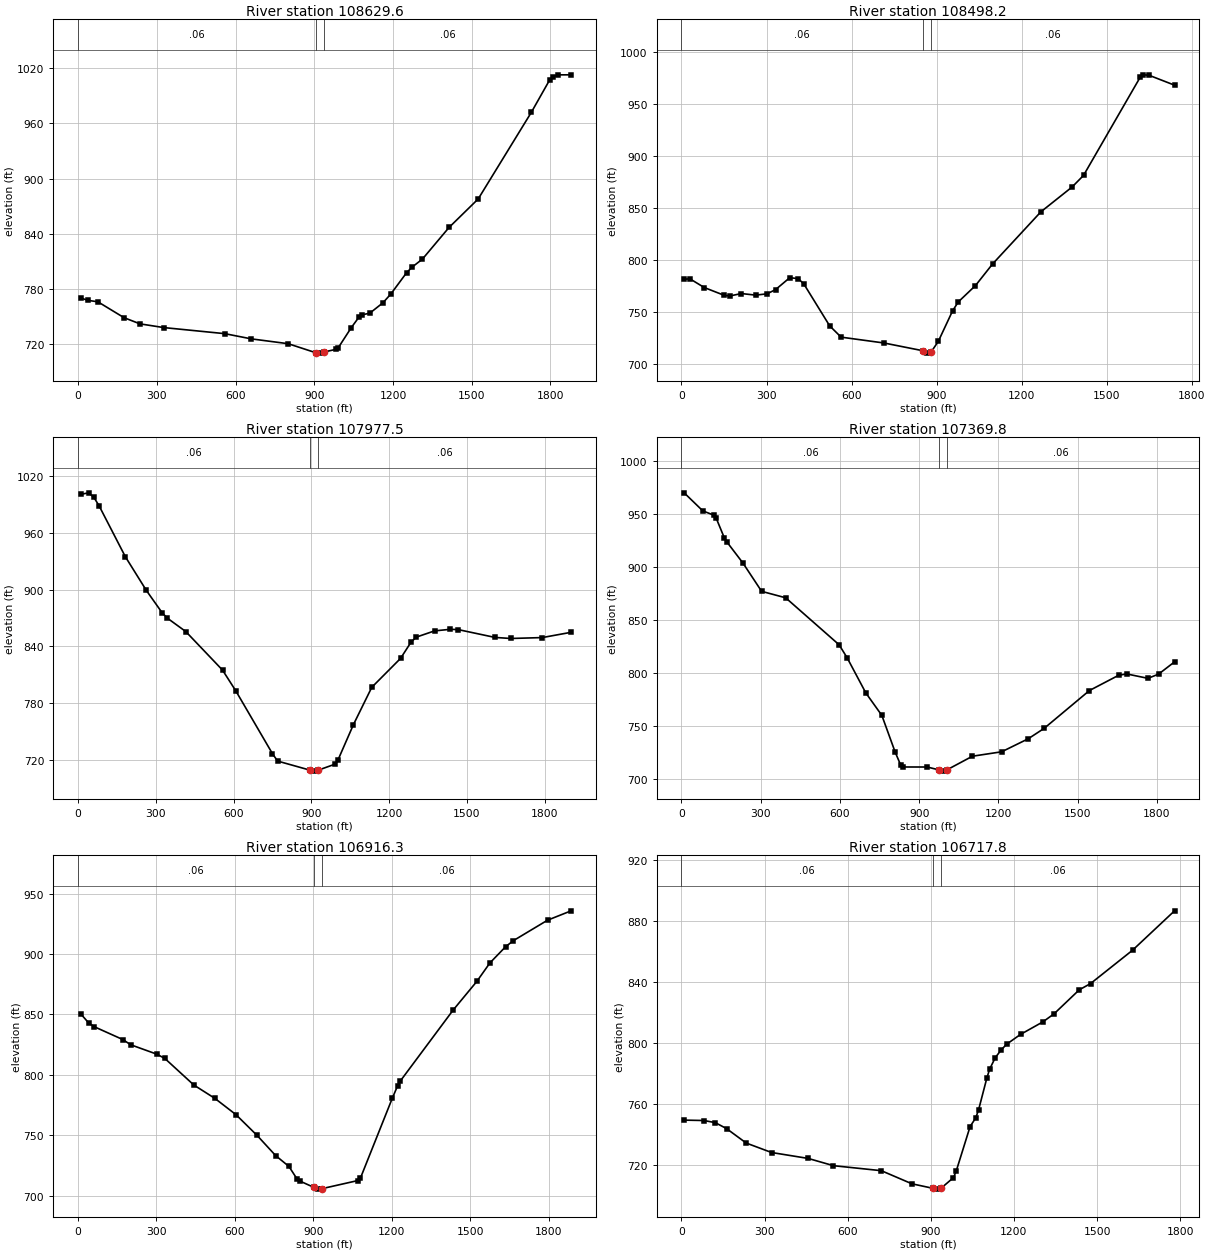
Type RM Length L Ch R = 1 ,108629.6,133.8,131.3,128.9
XS GIS Cut Line= 5
     1597863.421      440534.816     1597947.868      440536.516
     1598519.958      440599.799     1599145.993      440742.255
     1599655.464      441012.282
#Sta/Elev= 30
     9.4  770.57    37.5  767.83    75.1  766.37   175.3  749.04   235.9  742.35
   326.8   738.3   559.1  731.71     660  726.05   800.5  720.81   905.9     711
   920.9  710.57   935.9  711.72   981.1  714.58   991.1   716.3  1041.3  738.36
  1071.3  750.04  1081.4  752.13  1111.5  753.93  1161.6  765.21  1191.7  774.73
  1251.9  797.91    1272  803.79  1312.2  812.69  1413.4  846.99  1524.6  877.97
    1727  971.98  1797.8 1007.64  1807.9 1010.38  1828.1 1012.72  1878.7 1012.75
#Mann= 3 , 0 , 0
       0     .06       0   905.9    .045       0   935.9     .06       0
Bank Sta=905.9,935.9
XS Rating Curve= 0 ,0
Exp/Cntr=0.3,0.1

Type RM Length L Ch R = 1 ,108498.2,519.2,520.8,522.4
XS GIS Cut Line= 4
     1597940.767      440603.955     1598598.243       440751.33
      1598917.89       440800.09     1599571.854      441151.534
#Sta/Elev= 30
    10.1  781.65    30.2   781.9    80.5  773.57   150.8   766.1     171  765.49
   211.2  767.81   261.5  766.29   301.7  767.52   331.9  771.58   382.1  783.06
   412.3  782.12   432.4  776.72   522.9  736.74   563.2   725.9   714.2   720.3
   850.8  712.89   865.8  710.54   880.8  711.64   906.2   721.9   956.7   751.3
   976.9  759.84  1037.3  775.49  1097.5  796.22    1268  846.35  1378.4  870.28
  1418.5  881.35  1619.2   976.1  1629.2  978.04  1649.3  977.65  1739.6   968.1
#Mann= 3 , 0 , 0
       0     .06       0   850.8    .045       0   880.8     .06       0
Bank Sta=850.8,880.8
XS Rating Curve= 0 ,0
Exp/Cntr=0.3,0.1

Type RM Length L Ch R = 1 ,107977.5,610.8,607.7,604.6
XS GIS Cut Line= 4
     1597659.254      441106.869     1598345.688       441168.13
     1598970.123      441369.097     1599526.599      441395.986
#Sta/Elev= 30
    10.1  1000.5    40.5 1002.14    60.8  997.46    81.1  988.44   182.4   934.7
   263.5   899.1   324.3  875.56   344.6  869.83   415.5  855.72   557.4  815.01
   608.1  793.32   749.7  726.92   769.9  718.99   896.2   709.3   911.2  708.38
   926.2  709.36   991.9  715.79    1002  719.64  1062.6  757.59  1133.2  796.86
  1244.2  827.36  1284.6  844.49  1304.8  849.82  1375.5  856.42  1436.3  858.08
  1466.7  857.76  1608.5  849.51  1669.3  848.39  1790.8  849.35  1902.3  854.92
#Mann= 3 , 0 , 0
       0     .06       0   896.2    .045       0   926.2     .06       0
Bank Sta=896.2,926.2
XS Rating Curve= 0 ,0
Exp/Cntr=0.3,0.1

Type RM Length L Ch R = 1 ,107369.8,453.2,453.5,453.8
XS GIS Cut Line= 3
     1597647.235      441772.321     1598546.915      441798.408
     1599513.253        441800.8
#Sta/Elev= 30
    10.1  970.41    80.9  953.33   121.4  949.43   131.5  946.44   161.8   928.1
   171.9  924.01   232.6  904.13   303.4   877.4   394.4  871.31   596.7  826.94
     627   814.7   697.8   781.5   758.5  760.25     809  725.51   829.3   713.7
   839.4  711.57   930.3  711.54   975.7  708.77   990.7  707.66  1005.7  708.98
  1101.4  721.74  1212.1  725.92  1312.8  738.24  1373.2   748.1  1544.3  783.76
    1655  798.18  1685.2  799.43  1765.7  795.27    1806  799.23  1866.4  810.81
#Mann= 3 , 0 , 0
       0     .06       0   975.7    .045       0  1005.7     .06       0
Bank Sta=975.7,1005.7
XS Rating Curve= 0 ,0
Exp/Cntr=0.3,0.1

Type RM Length L Ch R = 1 ,106916.3,200,198.5,197
XS GIS Cut Line= 4
     1597656.656      442137.081     1598245.204      442216.032
     1599106.494      442244.742     1599530.169      442165.957
#Sta/Elev= 30
    10.1  850.43    40.3  842.96    60.4  839.91   171.1  829.15   201.3  824.84
   301.9     817   332.1  813.48   442.8  791.54   523.4  780.46     604  767.02
   685.1  749.76     756  733.09   806.7  724.16   837.1  713.99   847.3  712.17
   903.2  706.71   918.3  705.35   933.2  705.74  1070.3  712.44  1080.5  714.53
  1202.1  780.48  1222.4  790.74  1232.5  794.69  1435.3  853.61  1525.7  877.26
  1575.8  892.56    1636  906.02    1666  911.05  1796.3  927.93  1886.5  935.68
#Mann= 3 , 0 , 0
       0     .06       0   903.2    .045       0   933.2     .06       0
Bank Sta=903.2,933.2
XS Rating Curve= 0 ,0
Exp/Cntr=0.3,0.1

Type RM Length L Ch R = 1 ,106717.8,291.4,294.9,298.4
XS GIS Cut Line= 4
     1597724.104      442369.319     1598473.627      442427.572
     1598761.009      442388.737     1599498.882      442384.853
#Sta/Elev= 30
    10.2  749.36    81.3   749.1   121.9  747.71   162.5  743.81   233.7  734.29
   325.1  728.09   457.2   724.2   548.6  719.43   721.3  716.15   831.8  707.53
   906.8   704.6   921.8  704.03   936.8  704.58   981.8  711.61   991.8  715.97
  1041.8  745.16    1062   750.8  1072.1  755.91  1102.4  777.12  1112.5  782.93
  1132.7  790.41    1153  795.26  1173.2  799.16  1223.7  805.66  1304.6  813.91
    1345  819.22    1436  834.99  1476.4  839.04    1628  860.95  1779.7  886.85
#Mann= 3 , 0 , 0
       0     .06       0   906.8    .045       0   936.8     .06       0
Bank Sta=906.8,936.8
XS Rating Curve= 0 ,0
Exp/Cntr=0.3,0.1

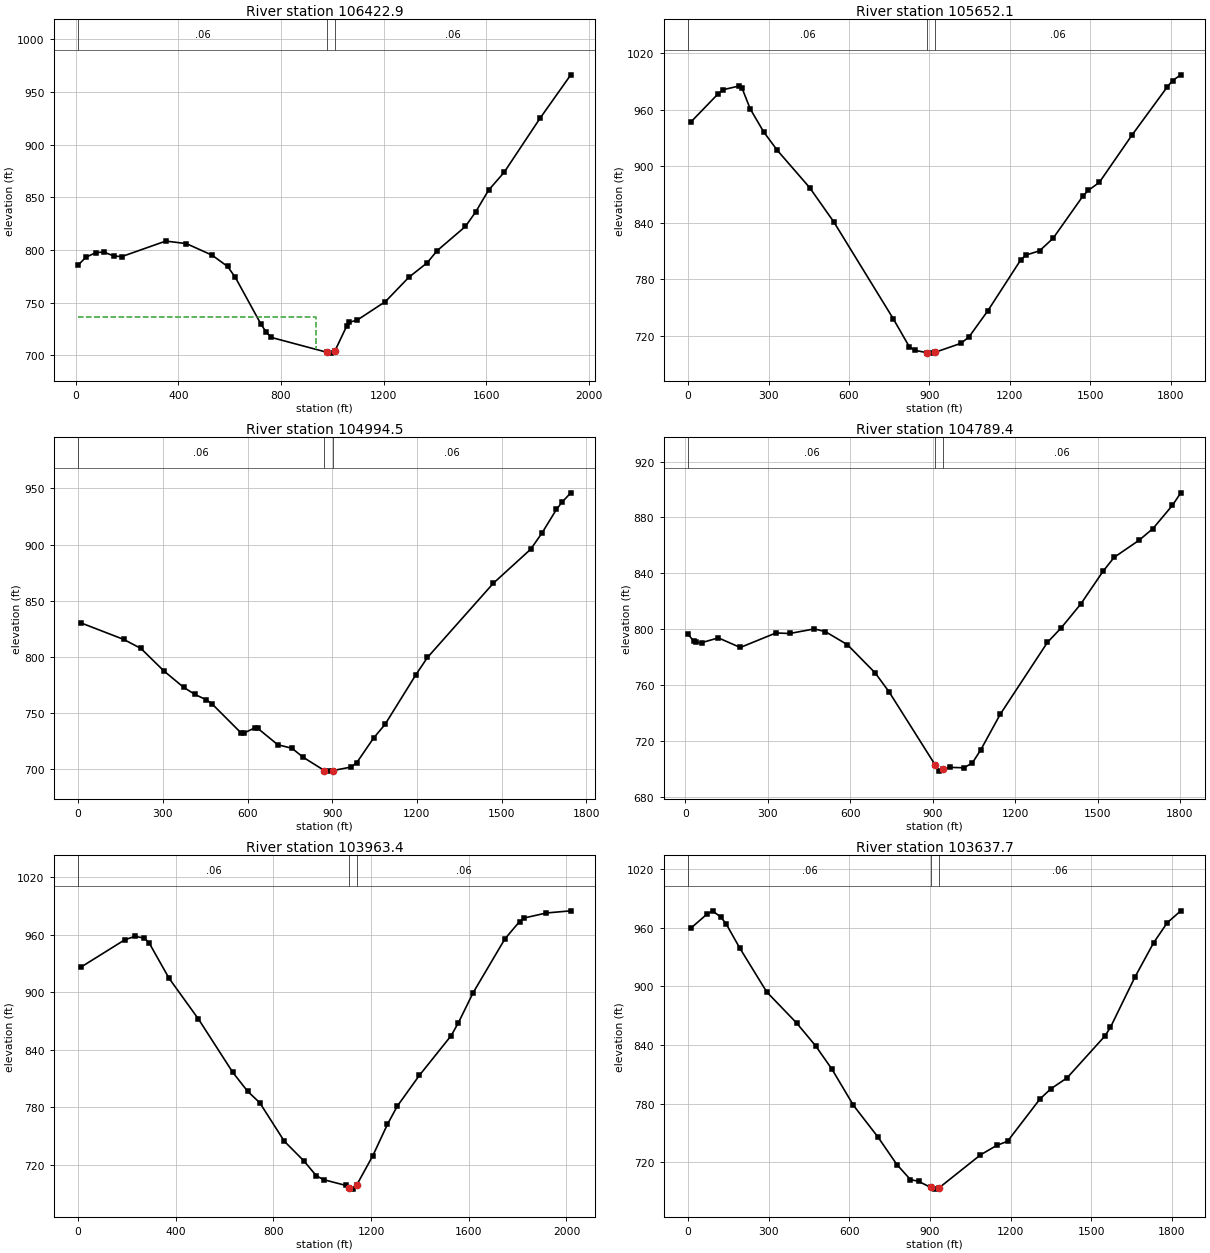
Type RM Length L Ch R = 1 ,106422.9,770.9,770.8,771
XS GIS Cut Line= 4
     1597716.449      442629.213     1598429.046      442618.601
     1599067.836      442769.326     1599489.995      443137.992
#Sta/Elev= 30
      10  785.65    40.2  793.15    80.3  797.61   110.4  797.96   150.6  794.17
   180.7  793.79   351.3  808.47   431.6  806.06     532  795.04   592.2  784.33
   622.3  773.99   722.8  729.28     743  721.87   763.2  716.87   980.4  702.72
   995.4     702  1010.4  704.06    1056  727.57  1066.1  731.34  1096.4  733.25
  1207.4  751.02  1298.3  774.05    1369  787.64    1409   799.4  1519.1  822.39
  1559.2  836.31  1609.2  856.87  1669.3  873.63  1809.4  925.07  1929.5  966.43
#Mann= 3 , 0 , 0
      10     .06       0   980.4    .045       0  1010.4     .06       0
#XS Ineff= 2 , 0
          936.07  736.03
Permanent Ineff=
       F       F
Bank Sta=980.4,1010.4
XS Rating Curve= 0 ,0
Exp/Cntr=0.3,0.1

Type RM Length L Ch R = 1 ,105652.1,659.4,657.6,655.5
XS GIS Cut Line= 3
     1597537.249      443185.187     1598419.315      443390.856
     1599321.586      443624.712
#Sta/Elev= 30
    10.1  946.93   110.7  976.56   130.8  981.26   191.2  985.25   201.3  982.72
   231.5  960.87   281.8  936.44   332.1  917.04   452.9  877.41   543.4  840.87
   764.8  738.26   825.2  708.32   845.3  704.59   890.7  702.11   905.7   701.6
   920.7  702.45  1017.2  711.95  1047.6  718.75  1118.5  746.79  1240.1   800.3
  1260.3   805.7    1311  810.21  1361.6  823.57  1473.1  868.49  1493.3  874.43
  1533.9  882.84  1655.4  932.91  1787.2   984.1  1807.4  990.93  1837.8  997.03
#Mann= 3 , 0 , 0
       0     .06       0   890.7    .045       0   920.7     .06       0
Bank Sta=890.7,920.7
XS Rating Curve= 0 ,0
Exp/Cntr=0.3,0.1

Type RM Length L Ch R = 1 ,104994.5,205.3,205.1,204.9
XS GIS Cut Line= 4
     1597432.838      444012.057     1598190.129      444027.591
     1598628.969      444047.009     1599176.548      444074.193
#Sta/Elev= 30
    10.1  830.31   161.6   815.6   222.2  807.61     303  787.72   373.7  772.98
   414.1  766.64   454.5  761.83   474.7  758.14   575.7  732.77   585.8  732.14
   626.2  737.01   636.3  736.48     707  721.94   757.4  718.77   797.4  710.69
   872.2  698.99   887.2  698.45   902.2  698.93   967.1  702.11   987.1  706.11
    1047  728.08  1086.9  739.97  1196.7  784.38  1237.3   799.6  1470.8  865.66
  1602.8  895.85  1643.4  910.48  1694.2  931.31  1714.5  937.92    1745  946.06
#Mann= 3 , 0 , 0
       0     .06       0   872.2    .045       0   902.2     .06       0
Bank Sta=872.2,902.2
XS Rating Curve= 0 ,0
Exp/Cntr=0.3,0.1

Type RM Length L Ch R = 1 ,104789.4,818.6,826,833.5
XS GIS Cut Line= 3
     1597378.852      444197.832     1597917.158      444226.542
     1599180.383      444262.429
#Sta/Elev= 30
      10  796.32    29.9  791.42    39.9  790.44    59.9  790.34   119.8  793.75
   199.7  786.87   329.4  797.27   379.3  796.88   469.2  800.16   509.1  798.26
   589.6  788.86   690.7  768.64   741.3  755.06   908.2  703.02  923.21  698.34
   938.2  699.64   963.7  701.03  1014.2  700.73  1044.6   704.3  1074.9  713.58
  1145.7  739.03  1317.5  790.51  1368.1  801.03  1438.9     818  1519.7  841.36
  1560.2   851.4  1651.2  863.67  1701.7  872.04  1772.5  888.66  1802.8   897.6
#Mann= 3 , 0 , 0
      10     .06       0   908.2    .045       0   938.2     .06       0
Bank Sta=908.2,938.2
XS Rating Curve= 0 ,0
Exp/Cntr=0.3,0.1

Type RM Length L Ch R = 1 ,103963.4,319.8,325.7,331.7
XS GIS Cut Line= 4
     1597380.316      444541.619     1598230.849      444850.143
      1598618.43      445230.546     1598927.331      445709.522
#Sta/Elev= 30
    10.1  925.86     191  954.53   231.2  957.99   271.4  956.45   291.5  950.89
     372  914.52   492.6  872.02   633.3  816.48   693.7  796.89   743.9  784.79
   844.4  744.75   924.9  724.18   975.2  708.87  1005.3  704.76  1095.8  698.79
    1111  696.34    1126   694.9    1141  699.22  1206.5  729.51  1266.8  762.39
    1307  781.26  1397.5  813.33  1527.8   854.7  1557.8  868.38  1617.8  899.43
  1747.8   955.4  1807.8   973.5  1827.8  977.29  1917.8  982.44  2017.8  984.68
#Mann= 3 , 0 , 0
       0     .06       0    1111    .045       0    1141     .06       0
Bank Sta=1111,1141
XS Rating Curve= 0 ,0
Exp/Cntr=0.3,0.1

Type RM Length L Ch R = 1 ,103637.7,219,211.4,203.7
XS GIS Cut Line= 4
     1597394.003      444633.423     1598096.924      445087.798
     1598139.643      445293.625     1598803.728      445713.048
#Sta/Elev= 30
    10.1  959.63    70.6  974.15    90.8   977.3     121  971.09   141.2  964.12
   191.6  939.46   292.4  894.37   403.4  862.65     474  839.34   534.5  815.58
   615.1  778.32   705.9  746.03   776.5  717.82   826.9  702.43     857  700.65
   902.1  694.48   917.1  692.67   932.1  693.68  1087.5  727.69  1147.9  737.38
  1188.2  741.63    1309  784.95  1349.3   795.3  1409.7  806.49  1550.7  849.39
  1570.8   858.1  1661.5  909.25    1732  944.87  1782.3   965.2  1832.7  977.39
#Mann= 3 , 0 , 0
       0     .06       0   902.1    .045       0   932.1     .06       0
Bank Sta=902.1,932.1
XS Rating Curve= 0 ,0
Exp/Cntr=0.3,0.1

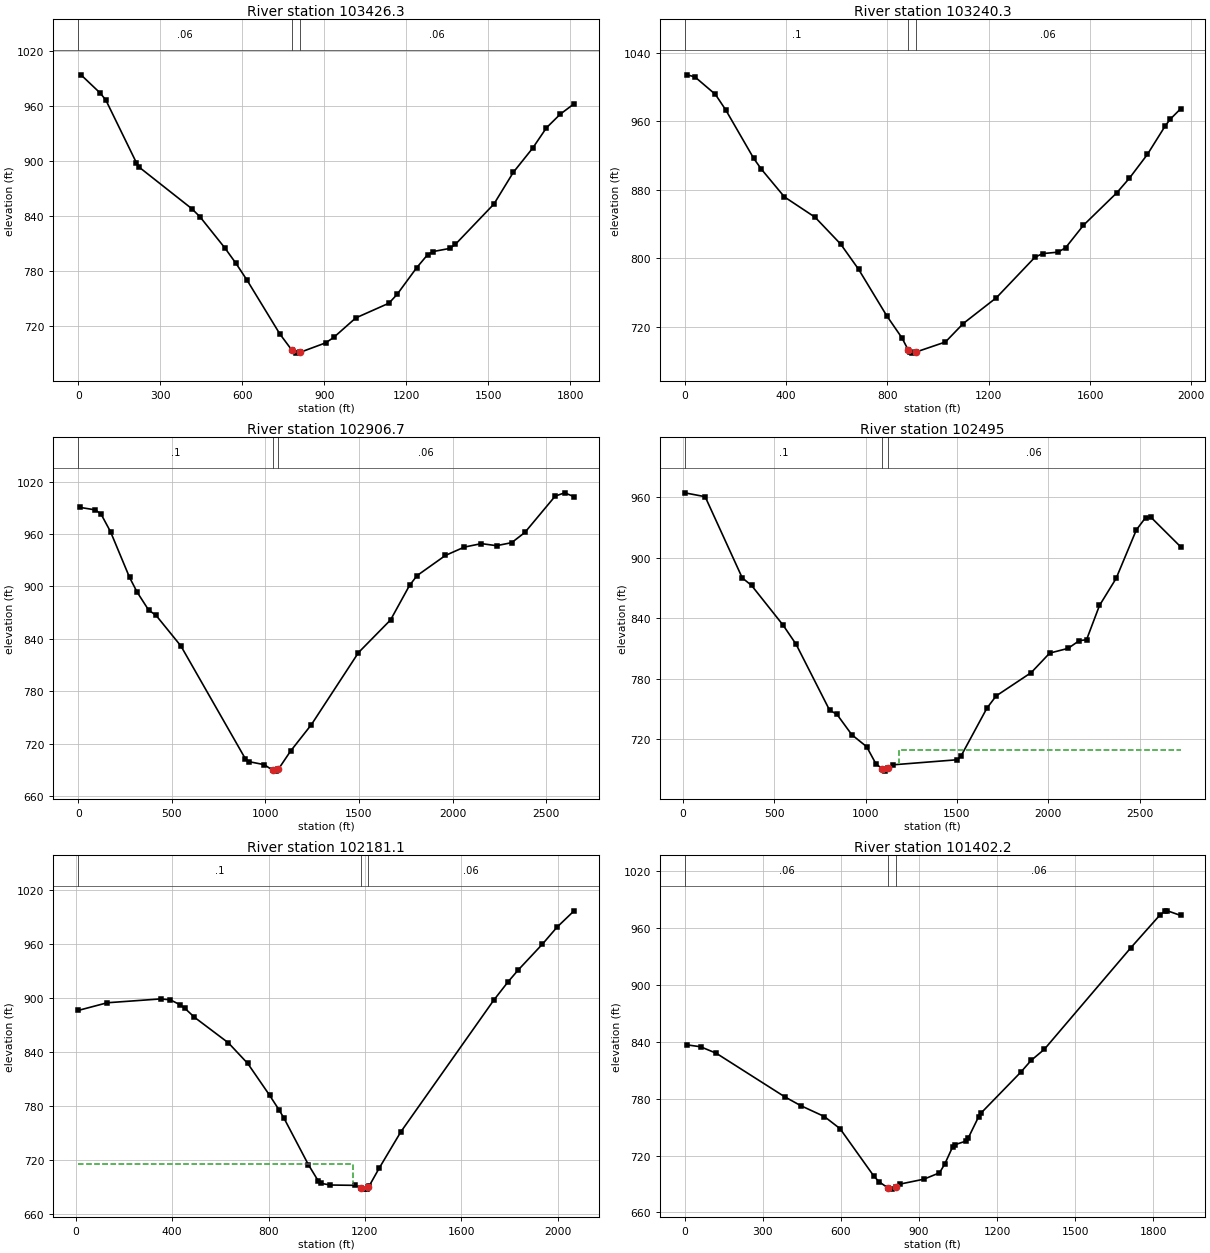
Type RM Length L Ch R = 1 ,103426.3,189.3,186,182.6
XS GIS Cut Line= 4
     1597320.216      444765.464     1597860.028      445208.187
     1598069.739      445355.762     1598815.379      445782.951
#Sta/Elev= 30
    10.1  994.49    80.9  974.45   101.2  966.85   212.5  898.78   222.6  893.79
   414.8  848.57   445.2  839.63   536.3  805.61   576.7  788.88   617.2  770.58
   737.6  711.65   781.8  693.93   796.8  690.77   811.8  691.66   905.3     702
   934.8  707.94  1015.2  729.17  1136.6  745.26  1166.9  755.04  1237.7  783.84
  1278.1  798.22  1298.3  801.62    1359  805.04  1379.2  809.36  1520.7  853.48
  1591.5  888.05  1662.3  914.45  1712.8  936.68  1763.4  951.57  1813.9  962.89
#Mann= 3 , 0 , 0
       0     .06       0   781.8    .045       0   811.8     .06       0
Bank Sta=781.8,811.8
XS Rating Curve= 0 ,0
Exp/Cntr=0.3,0.1

Type RM Length L Ch R = 1 ,103240.3,335.7,333.6,331.5
XS GIS Cut Line= 4
     1596988.945      445254.996     1597635.124      445366.917
     1598187.785       445524.82     1598815.629      445891.025
#Sta/Elev= 30
    10.1 1014.13    40.4 1011.65   121.1  991.25   161.4  973.36   272.4  916.52
   302.7   903.9   393.5  871.59   514.6  847.85   615.4  816.57   686.1  787.18
     797     733   857.5     707   882.8  692.54   887.7  690.18   897.8  689.24
   912.8  690.53  1028.9  702.22  1099.5  723.82  1230.6  754.05    1382   801.1
  1412.3  805.41  1472.9   807.1  1503.1  812.16  1573.8   838.5    1705  876.27
  1755.5  893.56  1826.2   921.2  1896.8  954.57    1917  962.54  1957.4  974.46
#Mann= 3 , 0 , 0
       0      .1       0   882.8    .045       0   912.8     .06       0
Bank Sta=882.8,912.8
XS Rating Curve= 0 ,0
Exp/Cntr=0.3,0.1

Type RM Length L Ch R = 1 ,102906.7,404.9,411.8,418.7
XS GIS Cut Line= 4
     1596959.596      445345.488     1597685.366      445732.965
     1598417.462      445797.562     1599400.768      446271.271
#Sta/Elev= 30
    10.2  990.48    91.4  987.65   121.9  982.86   172.7  962.63   274.2  910.37
   314.9  893.45   375.8  873.09   416.4  866.76   548.5  831.88   893.2  702.63
   913.3  699.37   993.9  695.98  1039.3  689.57  1054.3  688.58  1069.3  690.78
  1134.8  711.61  1245.6  741.78  1497.3  824.32  1668.8  861.72  1769.9  901.16
  1810.3  912.43  1961.9  935.51    2063  945.08  2153.9  949.02  2234.8  946.68
  2315.6  950.13  2386.4  961.86  2548.1 1003.41  2598.6 1007.18  2649.1 1002.71
#Mann= 3 , 0 , 0
       0      .1       0  1039.3    .045       0  1069.3     .06       0
Bank Sta=1039.3,1069.3
XS Rating Curve= 0 ,0
Exp/Cntr=0.3,0.1

Type RM Length L Ch R = 1 ,102495  ,309.5,313.8,318.1
XS GIS Cut Line= 4
     1596988.391      445425.102     1597634.358      445934.698
     1598050.649      446322.279     1598632.019      447520.907
#Sta/Elev= 30
    10.2  964.18   121.9  960.35     325  879.87   375.8  872.42   548.5  833.04
   619.6   814.1   802.5  748.92   843.1  744.66   924.3   724.5  1005.6  712.61
  1056.4  695.64  1092.2  690.56 1106.84  688.41  1122.2  691.03  1147.8  694.64
  1502.6   699.7  1522.8  703.62  1664.1  750.92  1714.5  762.96  1906.3  786.07
  2007.2  805.35  2108.1  810.07  2168.7  817.67    2209  818.63  2279.7  852.55
  2370.5  879.29  2481.5  927.47    2532  939.64  2562.3  939.79  2723.7  910.72
#Mann= 3 , 0 , 0
    10.2      .1       0  1092.2    .045       0  1122.2     .06       0
#XS Ineff= 2 , 0
                         1181.81          709.66
Permanent Ineff=
       F       F
Bank Sta=1092.2,1122.2
XS Rating Curve= 0 ,0
Exp/Cntr=0.3,0.1

Type RM Length L Ch R = 1 ,102181.1,781.6,778.9,776.2
XS GIS Cut Line= 4
     1596804.933      445476.402     1597477.221      446020.062
     1597671.011      446486.594      1597728.43      447182.803
#Sta/Elev= 30
    10.1  886.24   130.7  894.78   351.9  899.05   392.1  898.11   432.3  892.61
   452.4   888.7   492.6  878.61   633.4  850.15   713.8  827.18   804.3  791.88
   844.5  775.17   864.6   766.1   965.6  714.47  1006.1  696.58  1016.2  693.79
  1056.6  691.87  1157.6   691.5    1183  688.95    1198  687.29  1208.1  687.82
    1213  689.34  1218.2  690.94  1258.6  710.28  1349.6  751.21  1734.3  897.43
    1795  918.31  1835.5  930.98  1936.7  959.97  1997.5  978.92  2068.4  997.13
#Mann= 3 , 0 , 0
    10.1      .1       0    1183    .045       0    1213     .06       0
#XS Ineff= 2 , 0
          1150.7  714.92
Permanent Ineff=
       F       F
Bank Sta=1183,1213
XS Rating Curve= 0 ,0
Exp/Cntr=0.3,0.1

Type RM Length L Ch R = 1 ,101402.2,500.6,498.3,496.1
XS GIS Cut Line= 4
     1596515.448      445704.256      1596702.06      446206.674
     1597039.399      446644.497     1597426.979      447362.238
#Sta/Elev= 30
    10.1   836.8    60.7  834.87   121.3  827.97   384.3  781.97   444.9  772.76
     536   761.2   596.3   748.4   726.9  698.01     747  692.13   782.2  685.48
   797.2  684.51   812.2  687.08   827.4  689.87   917.8  694.97   978.1  701.68
   998.2  710.78  1028.4  728.86  1038.4  731.49  1078.6  735.12  1088.7  738.45
  1128.9  761.09    1139  765.17  1290.1  807.89  1330.4   820.5  1380.7  832.08
    1713  939.37  1823.8  973.63  1843.9  977.87    1854  978.42  1904.4  973.53
#Mann= 3 , 0 , 0
       0     .06       0   782.2    .045       0   812.2     .06       0
Bank Sta=782.2,812.2
XS Rating Curve= 0 ,0
Exp/Cntr=0.3,0.1