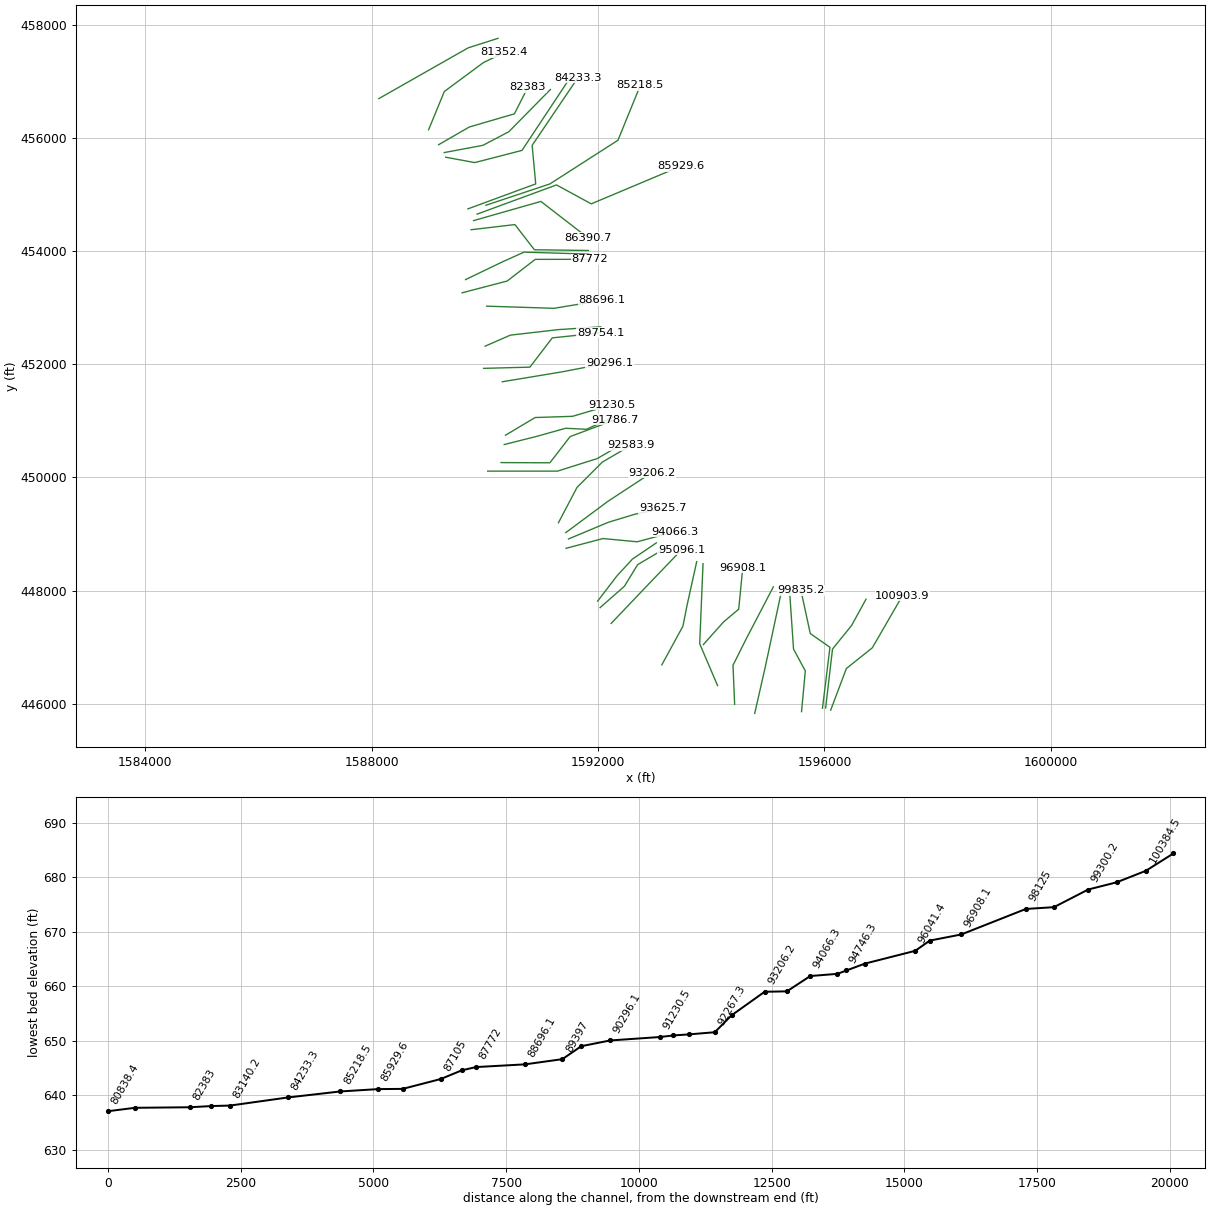
HEC-RAS study BEECHFK.prj: BEECHFK

--- BEECHFK.g01 (geometry) --- (continued)

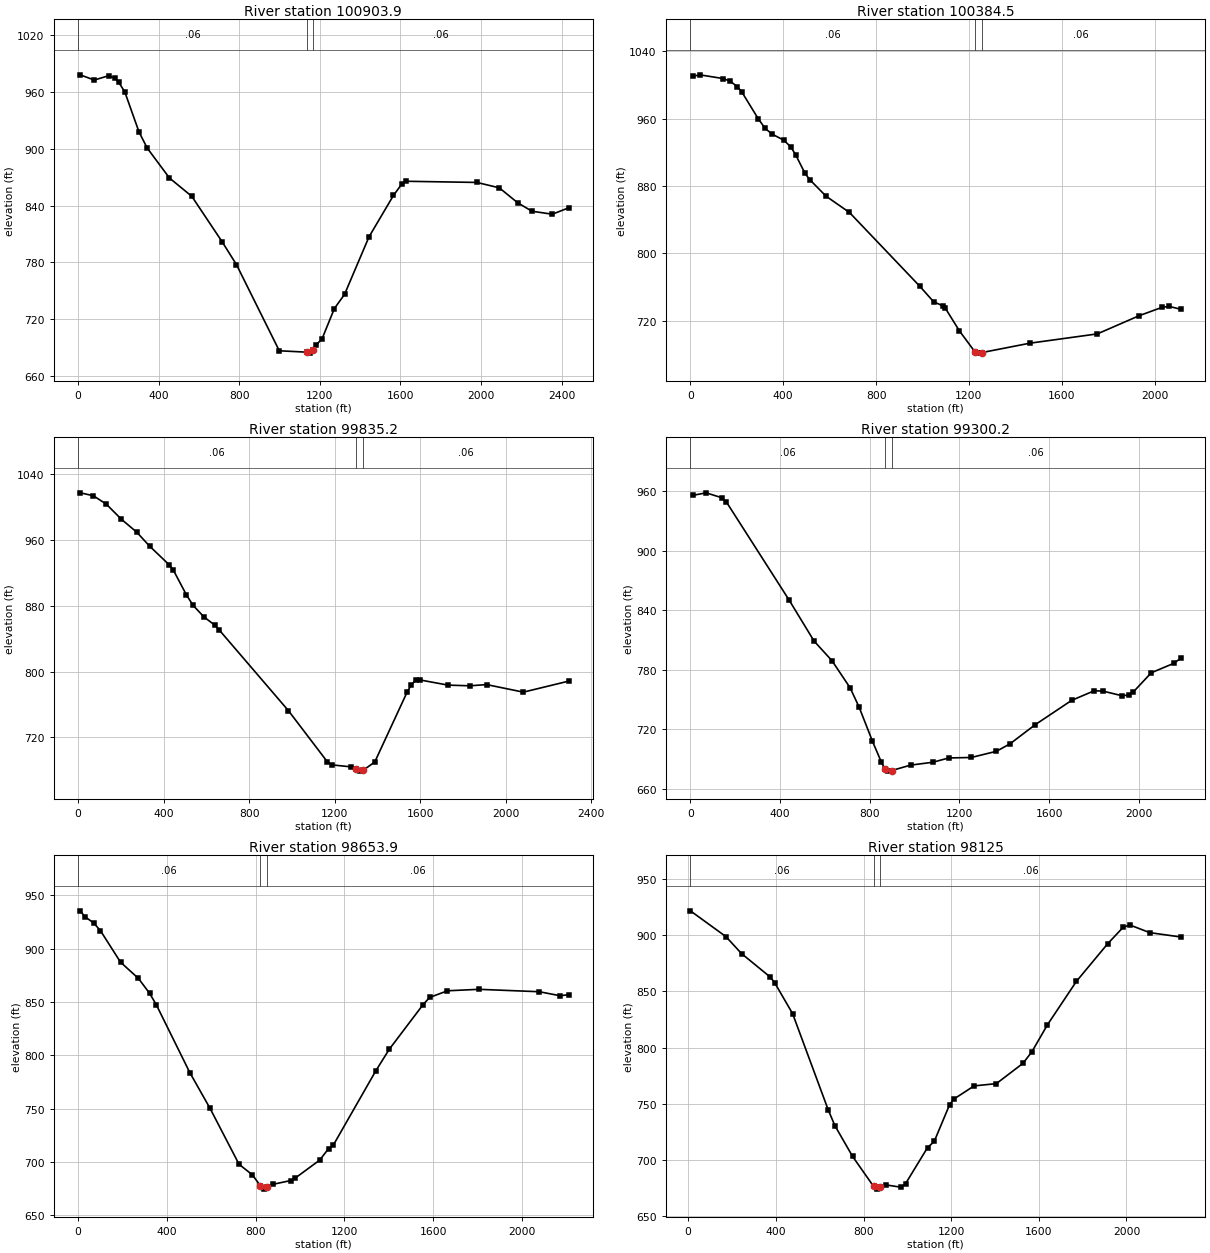
Type RM Length L Ch R = 1 ,100903.9,517.1,519.4,521.6
XS GIS Cut Line= 4
     1596109.738      445887.047     1596386.854      446622.738
     1596845.609      446989.013     1597376.737      447907.722
#Sta/Elev= 30
    10.1  977.95    80.6  972.44   151.2  976.98   181.4  974.51   201.6  970.15
   231.8  959.99   302.4  917.72   342.7  900.85   453.5  869.14   564.4   849.8
   715.6  801.66   786.2  777.74   998.7  686.88  1135.5  685.41  1150.5   684.4
  1165.5  687.47  1180.9  692.85  1211.2  699.61    1272   731.4  1322.6  746.39
  1443.9  807.03  1565.2  850.69  1605.6  862.43  1625.9  865.68  1979.6  864.44
  2090.8  858.73  2181.7  843.02  2252.5  834.09  2353.5  830.93  2434.4  837.61
#Mann= 3 , 0 , 0
       0     .06       0  1135.5    .045       0  1165.5     .06       0
Bank Sta=1135.5,1165.5
XS Rating Curve= 0 ,0
Exp/Cntr=0.3,0.1

Type RM Length L Ch R = 1 ,100384.5,534.8,549.4,566.4
XS GIS Cut Line= 4
     1596020.548       445926.83     1596142.222       446967.48
      1596479.56       447383.77     1596734.452       447848.12
#Sta/Elev= 30
    10.1 1010.42    40.3 1012.24     141 1007.82   171.3 1004.64   201.5  998.35
   221.6  991.87   292.2  960.03   322.4  948.42   352.6  941.62     403  934.44
   433.2  926.23   453.3   917.2   493.6  895.17   513.8   887.7   584.3  867.91
   685.1  848.57   987.3  761.07  1047.7  742.37  1088.2  737.34  1098.3  734.72
  1158.9  707.77  1224.8  683.13  1239.8  681.21  1254.8  681.81  1462.2  693.01
  1753.5   704.1  1933.4  725.72  2033.3   735.8  2063.3  736.78  2113.3  733.34
#Mann= 3 , 0 , 0
       0     .06       0  1224.8    .045       0  1254.8     .06       0
Bank Sta=1224.8,1254.8
XS Rating Curve= 0 ,0
Exp/Cntr=0.3,0.1

Type RM Length L Ch R = 1 ,99835.2 ,539.6,535,530.3
XS GIS Cut Line= 4
     1595965.029      445921.312     1596096.957      446998.549
     1595749.375      447240.703     1595583.092      448008.486
#Sta/Elev= 30
    10.1  1017.3      71 1013.82   131.9  1003.6   202.9  985.12   273.9  969.63
   334.7  952.51     426  929.88   446.3  923.07   507.1  893.18   537.6  880.72
   588.3   866.6     639  856.57   659.3  850.93   983.9  752.63    1166  690.47
  1186.1  686.72  1276.9   684.3  1302.3  681.52  1317.3   679.1  1332.3  679.89
  1387.9  690.21  1539.1  775.01  1559.3  784.28  1579.4  789.32  1599.5  789.91
  1730.5  783.63  1831.2   782.8  1911.8  784.23    2083  775.08  2294.5  788.44
#Mann= 3 , 0 , 0
       0     .06       0  1302.3    .045       0  1332.3     .06       0
Bank Sta=1302.3,1332.3
XS Rating Curve= 0 ,0
Exp/Cntr=0.3,0.1

Type RM Length L Ch R = 1 ,99300.2 ,653.4,646.3,639.2
XS GIS Cut Line= 4
     1595595.013      445860.865     1595661.335        446579.9
      1595453.19       446967.48     1595383.532      447990.908
#Sta/Elev= 30
      10  955.89    70.2  958.48   140.4   953.5   160.5  949.28   441.3  849.98
   551.6  808.98   631.8  789.08   712.1  761.93   752.1  742.59   812.1  707.91
   852.1   686.7   867.1  680.26   882.1  677.78   897.1  678.34     982  683.82
    1082  686.76    1152  691.05  1253.4  691.56  1365.2   697.8  1426.1  705.39
  1537.8  724.58  1700.3  749.11  1801.9  758.91  1842.5  758.37  1923.8  753.88
  1954.2  754.44  1974.5  757.36  2055.8  776.99  2157.3  786.61  2187.8   791.8
#Mann= 3 , 0 , 0
       0     .06       0   867.1    .045       0   897.1     .06       0
Bank Sta=867.1,897.1
XS Rating Curve= 0 ,0
Exp/Cntr=0.3,0.1

Type RM Length L Ch R = 1 ,98653.9 ,531.4,528.9,526.3
XS GIS Cut Line= 3
     1594767.359      445830.296     1594950.698      446635.966
     1595240.313      447989.754
#Sta/Elev= 30
    10.1  935.59    30.2  930.15    70.5   924.2   100.8     917   191.5   887.4
   272.1  872.18   322.4  858.22   352.7  847.47   503.8  783.79   594.5  750.43
   725.5  697.86     786  687.87   821.4  677.78   836.4  674.54   851.4  676.15
   876.8  678.98   957.6  682.55   977.8  684.76    1089  701.76  1129.4   712.6
  1149.6  715.51  1341.6  785.39  1402.3  805.65  1553.8  847.29  1584.2  854.31
    1665  860.59  1806.5  861.96  2079.3   859.7  2170.3  856.02  2210.7   856.8
#Mann= 3 , 0 , 0
       0     .06       0   821.4    .045       0   851.4     .06       0
Bank Sta=821.4,851.4
XS Rating Curve= 0 ,0
Exp/Cntr=0.3,0.1

Type RM Length L Ch R = 1 ,98125   ,1221.1,1216.9,1212.8
XS GIS Cut Line= 4
     1594412.465      445991.352     1594383.755      446680.384
     1594613.433      447139.738     1595096.711      448066.315
#Sta/Elev= 30
    10.1  921.59   172.4  898.65   243.4  883.59   375.2  862.61   395.5  857.39
   476.7  830.12   638.9   744.7   669.3  730.68   750.1   703.3   845.8   676.7
  860.95  674.21   875.8  675.83   901.1     678   971.6   675.9   991.7  679.01
  1092.4  711.19  1122.6  716.55  1193.1  749.41  1213.3   754.4  1304.7  765.97
  1406.1  767.98  1527.9  786.07  1568.5  796.38  1639.5  820.35  1771.4  858.88
  1913.4  892.16  1984.4   906.9  2014.9  909.04  2106.2  902.19  2248.2  898.32
#Mann= 3 , 0 , 0
    10.1     .06       0   845.8    .045       0   875.8     .06       0
Bank Sta=845.8,875.8
XS Rating Curve= 0 ,0
Exp/Cntr=0.3,0.1

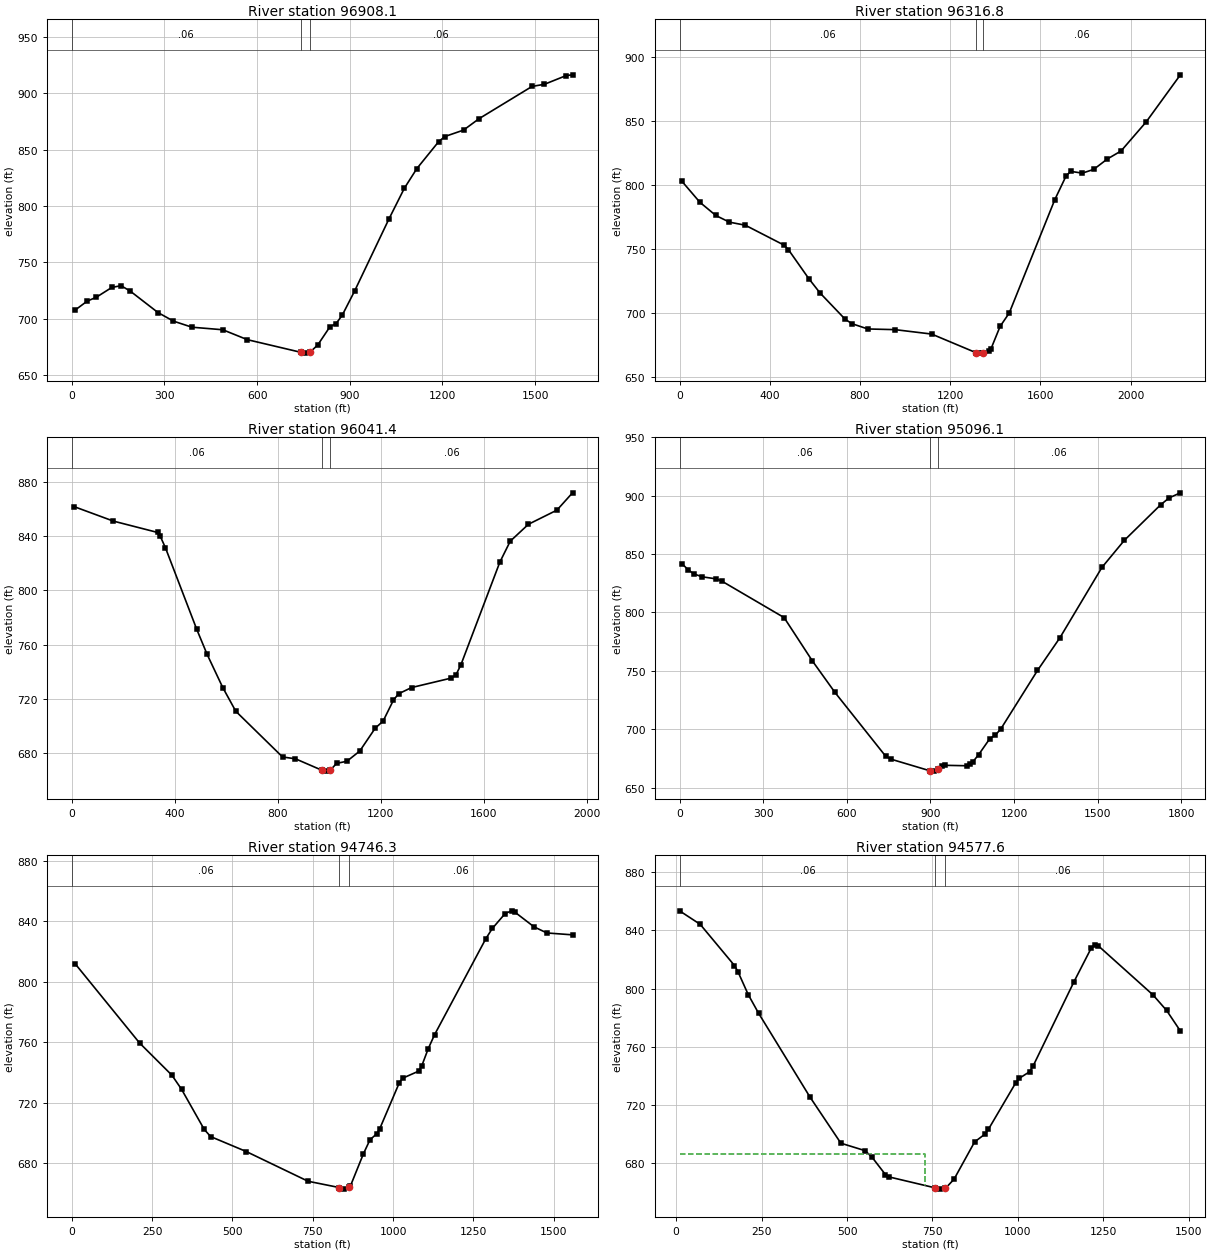
Type RM Length L Ch R = 1 ,96908.1 ,582.7,591.3,599.9
XS GIS Cut Line= 4
     1593859.804      447046.432     1594218.675      447448.367
     1594484.239      447670.867     1594556.013      448402.963
#Sta/Elev= 30
      10  707.52    49.9  715.63    79.8  719.15   129.7   727.8   159.7  729.39
   189.6  724.54   279.4   705.5   329.3  697.93   389.2  692.53   488.9  690.27
   568.5  681.47   741.6  670.26   756.6  669.53   771.6  670.44   796.2  676.73
   835.8  692.93   855.6  695.77   875.4  703.06   915.5  724.57  1026.4  788.39
  1076.7  815.88  1117.1  833.31  1187.6  857.18  1207.7  861.75  1268.2  867.45
  1318.6  877.61  1489.9   906.2  1530.2  908.12  1600.7  915.87  1620.9   916.5
#Mann= 3 , 0 , 0
       0     .06       0   741.6    .045       0   771.6     .06       0
Bank Sta=741.6,771.6
XS Rating Curve= 0 ,0
Exp/Cntr=0.3,0.1

Type RM Length L Ch R = 1 ,96316.8 ,276.9,275.4,273.8
XS GIS Cut Line= 3
     1594111.014      446321.513     1593795.207      447060.787
     1593853.947      448476.101
#Sta/Elev= 30
      10   803.1    90.4  786.52   160.8  776.22   221.1     771   291.4  768.61
   462.2   753.1   482.3  749.54   572.8   726.8     623  715.49   733.6  695.05
   763.7  691.51   834.3  687.34   955.7   686.8  1117.6  683.35    1315  668.71
    1330  668.41    1345   668.8  1370.5  669.95  1380.6  671.72  1421.1  689.33
  1461.6  699.83  1663.9  788.72  1714.5  807.49  1734.8  810.76  1785.4   809.4
  1835.9   812.3  1896.7  820.49  1957.4  826.75  2068.7   849.5  2220.4   886.4
#Mann= 3 , 0 , 0
       0     .06       0    1315    .045       0    1345     .06       0
Bank Sta=1315,1345
XS Rating Curve= 0 ,0
Exp/Cntr=0.3,0.1

Type RM Length L Ch R = 1 ,96041.4 ,951.1,945.4,939.7
XS GIS Cut Line= 4
     1593125.719      446687.589     1593498.812       447371.32
     1593572.599      447744.139     1593742.365       448511.85
#Sta/Elev= 30
    10.1  861.92   161.8  851.28   333.8  842.88   343.9  840.09   364.2  831.51
   485.5  771.38     526  752.78   586.7   728.3   637.3  710.78   818.9  676.99
   868.9  675.65   973.9  667.01   988.9  666.53  1003.9  667.13  1028.9  672.26
  1068.9  673.82  1118.9  681.38  1179.1  698.33  1209.4  703.44  1249.7  719.02
  1269.8  723.71  1320.2  728.29  1471.4  735.15  1491.6  737.31  1511.8  745.15
    1663  820.98  1703.3  836.42  1773.8  848.91  1884.7  859.39  1945.2  872.17
#Mann= 3 , 0 , 0
       0     .06       0   973.9    .045       0  1003.9     .06       0
Bank Sta=973.9,1003.9
XS Rating Curve= 0 ,0
Exp/Cntr=0.3,0.1

Type RM Length L Ch R = 1 ,95096.1 ,347.7,349.8,352
XS GIS Cut Line= 3
     1592230.531      447419.657     1592859.841      448080.427
     1593472.224      448718.769
#Sta/Elev= 30
    10.1   841.4    30.4   836.6    50.7  833.02    81.1   830.5   131.8  828.71
   152.1  826.74   375.1   795.6   476.5  758.53   557.6  731.55   740.1  676.79
   760.4   674.3   897.5  664.54   912.5  664.19   927.5  666.24   942.7  668.77
   952.7  669.17  1033.1  668.77  1043.2  669.88  1053.2  672.38  1073.3  678.33
  1113.5  692.05  1133.6  695.06  1153.7  700.64  1284.4  750.35  1364.8  778.32
  1515.6  838.54    1596  861.71  1726.7  892.23  1756.9  898.05  1797.1  902.37
#Mann= 3 , 0 , 0
       0     .06       0   897.5    .045       0   927.5     .06       0
Bank Sta=897.5,927.5
XS Rating Curve= 0 ,0
Exp/Cntr=0.3,0.1

Type RM Length L Ch R = 1 ,94746.3 ,170.6,168.6,166.7
XS GIS Cut Line= 4
     1592035.806      447699.332      1592465.79      448078.124
     1592698.802      448458.711      1593162.66       448732.88
#Sta/Elev= 30
    10.1  812.17   211.1  759.61   311.7   738.3   341.8  728.96   412.2  702.46
   432.3  697.68   542.9  687.81   735.3  668.14   831.9     664   846.9  662.93
   861.9  664.07   867.2  665.05   907.7  686.37     928  695.58   948.3  699.41
   958.4   702.9  1019.3  733.34  1029.3  736.28  1079.2  740.96  1089.1  744.48
  1109.1  755.78    1129  765.12  1288.7   828.7  1308.7  835.39  1348.6  845.25
  1368.5  847.03  1378.5  846.21  1438.4  836.43  1478.3  832.39  1558.1  831.14
#Mann= 3 , 0 , 0
       0     .06       0   831.9    .045       0   861.9     .06       0
Bank Sta=831.9,861.9
XS Rating Curve= 0 ,0
Exp/Cntr=0.3,0.1

Type RM Length L Ch R = 1 ,94577.6 ,520.6,511.3,502.1
XS GIS Cut Line= 4
     1591991.998      447814.043      1592333.75       448260.65
     1592605.597      448555.799     1593028.903      448843.181
#Sta/Elev= 30
      10  853.44    70.3  844.17   170.7  815.87   180.8  811.66   210.9  795.91
     241  783.19   391.6  725.53     482  693.85   552.3  688.76   572.4  684.45
   612.5  672.26   622.6  670.71     758  663.17     773  662.31     788  662.85
   813.2  669.16   873.3  694.75   903.4  700.06   913.5  703.33   993.7  735.36
  1003.8   738.4  1033.9  742.89  1043.9  746.63  1164.3  804.88  1214.4  827.82
  1224.5  829.99  1234.5  829.55    1395  795.73  1435.1     785  1475.3  770.92
#Mann= 3 , 0 , 0
      10     .06       0     758    .045       0     788     .06       0
#XS Ineff= 2 , 0
          729.26  686.77
Permanent Ineff=
       F       F
Bank Sta=758,788
XS Rating Curve= 0 ,0
Exp/Cntr=0.3,0.1

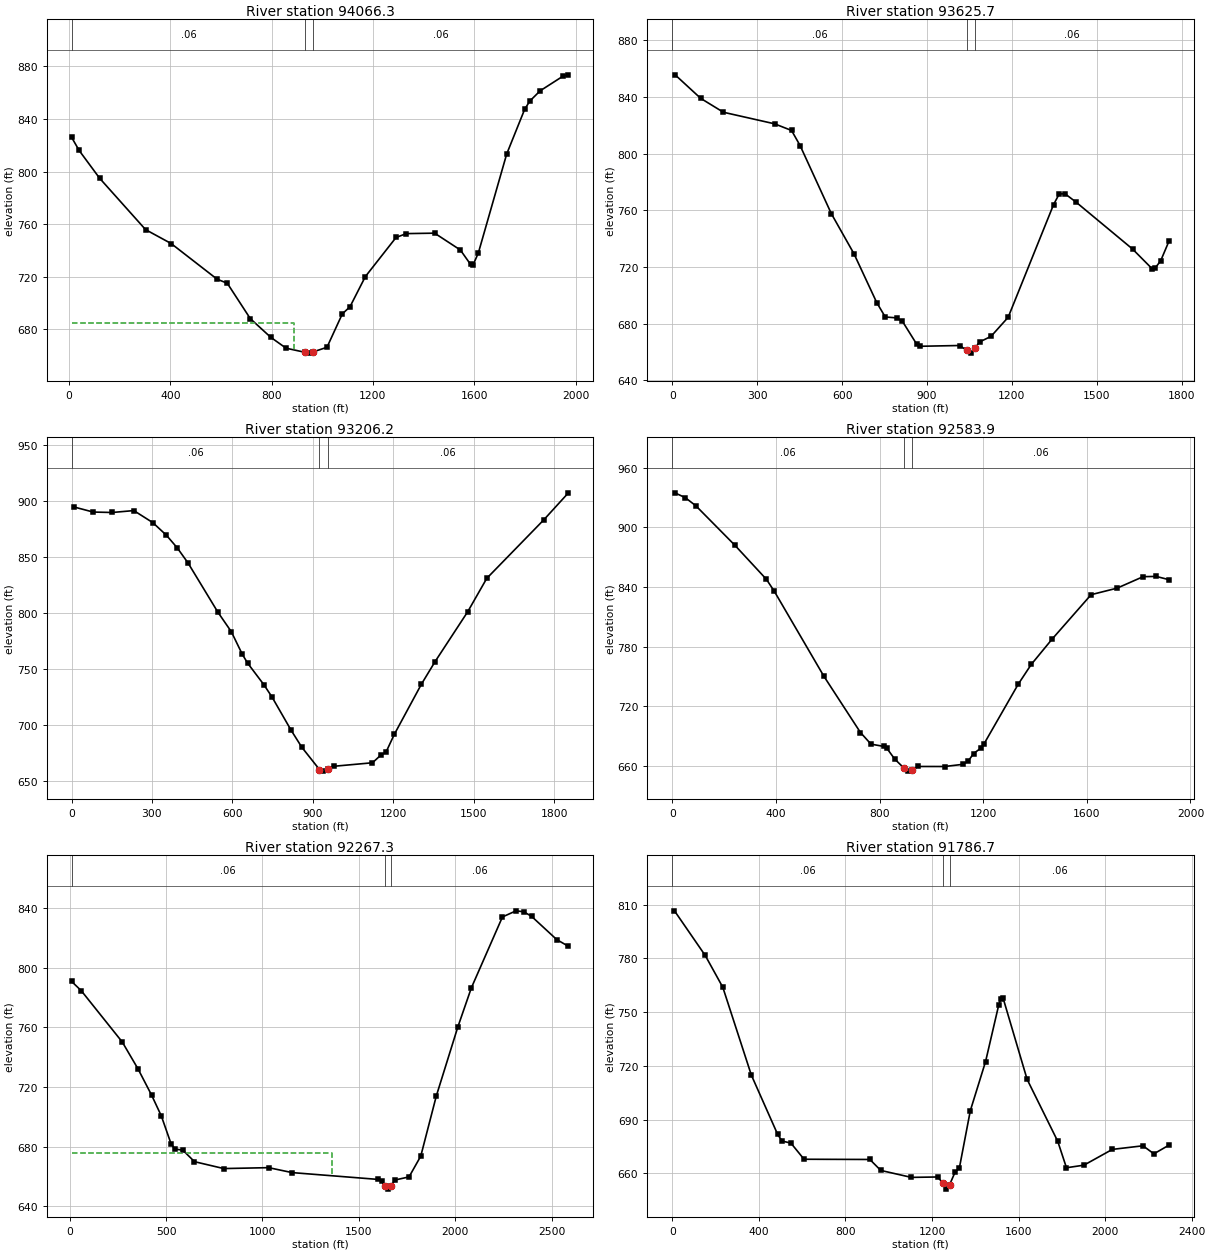
Type RM Length L Ch R = 1 ,94066.3 ,436.6,440.6,444.6
XS GIS Cut Line= 4
     1591433.838      448747.479     1592086.983      448919.737
     1592689.886      448862.318     1593356.784      449042.026
#Sta/Elev= 30
    10.1  826.15    40.3  816.01     121  794.93   302.5  755.83   403.3  745.27
   584.7  718.16   625.1  715.05   715.9  688.15   796.6  673.96   857.2  665.66
     933  662.48     948  661.91     963  662.78  1018.7  666.37  1079.2  691.76
  1109.5  697.19  1170.1   720.1  1291.3  749.86  1331.9   752.8  1443.6  753.14
  1545.2  740.34  1585.8  729.31    1596  729.26  1616.3  738.14    1728  813.27
  1799.1  847.34  1819.4   853.6  1860.1  861.38  1951.5  872.67  1971.8  873.55
#Mann= 3 , 0 , 0
    10.1     .06       0     933    .045       0     963     .06       0
#XS Ineff= 2 , 0
          888.19  684.67
Permanent Ineff=
       F       F
Bank Sta=933,963
XS Rating Curve= 0 ,0
Exp/Cntr=0.3,0.1

Type RM Length L Ch R = 1 ,93625.7 ,416.2,419.5,422.5
XS GIS Cut Line= 4
     1591476.903       448912.56     1592180.289      449206.834
     1592653.999      449350.382     1593142.063      449450.866
#Sta/Elev= 30
      10  855.55   100.3  838.95   180.6  829.13   361.2  820.98   421.4  816.27
   451.5  805.65   561.8   757.6   642.1  729.18   722.3  694.81   752.4  684.62
   792.8  683.98     813   681.6   863.5  665.43   873.6  663.93    1015  664.48
  1040.4  661.11  1055.4   659.1  1070.4  662.81  1085.7  666.98  1126.1  670.91
  1186.7  684.39  1347.1  763.92  1367.1  771.45    1387  771.68  1426.9  765.64
  1626.2  732.58  1695.9  718.56  1705.9  719.08  1725.8  724.37  1755.7   738.5
#Mann= 3 , 0 , 0
       0     .06       0  1040.4    .045       0  1070.4     .06       0
Bank Sta=1040.4,1070.4
XS Rating Curve= 0 ,0
Exp/Cntr=0.3,0.1

Type RM Length L Ch R = 1 ,93206.2 ,621,622.3,623.9
XS GIS Cut Line= 3
      1591428.86      449024.691     1592175.143      449578.587
     1592947.364      450084.937
#Sta/Elev= 30
    10.1  894.48    80.8  890.01   151.5  889.62   232.3  891.32   303.1  880.59
   353.6   869.4     394  858.16   434.4  844.65   545.5  800.84     596  783.28
   636.4  763.37   656.6  755.31   717.2   736.1   747.5  725.14   818.3  695.67
   858.7  680.31   924.5  660.46   939.5  659.02   954.5  661.25   980.1  663.39
  1122.2  666.48  1152.6  673.11  1172.9  676.08  1203.4   691.7  1304.8   736.6
  1355.6  756.67  1477.3  801.14  1548.4  830.91  1761.5   883.2  1852.8  907.15
#Mann= 3 , 0 , 0
       0     .06       0   924.5    .045       0   954.5     .06       0
Bank Sta=924.5,954.5
XS Rating Curve= 0 ,0
Exp/Cntr=0.3,0.1

Type RM Length L Ch R = 1 ,92583.9 ,320.3,316.5,312.8
XS GIS Cut Line= 4
      1591299.08      449199.178     1591627.628      449824.091
     1592072.628      450269.091     1592575.066      450564.101
#Sta/Elev= 30
    10.1  934.87    50.4  929.95    90.8  921.87   242.1  881.95   363.1  847.86
   393.4  835.92     585  750.27   726.3  693.58   766.9  681.88   817.7  679.51
   827.8  677.81   858.3  666.93     894  657.79     909   654.7     924  655.63
   949.6  659.37  1051.1  659.35  1122.2  661.55  1142.5  664.84  1162.8  672.43
  1193.2  678.21  1203.4  682.22  1335.3  742.22  1385.6  762.12  1465.9  787.57
  1616.6  832.33  1717.1  838.93  1817.5  850.47  1867.8  850.71    1918  847.39
#Mann= 3 , 0 , 0
       0     .06       0     894    .045       0     924     .06       0
Bank Sta=894,924
XS Rating Curve= 0 ,0
Exp/Cntr=0.3,0.1

Type RM Length L Ch R = 1 ,92267.3 ,474.6,480.6,486.6
XS GIS Cut Line= 4
     1590048.597      450111.188     1591283.113      450111.188
     1591986.499      450333.688      1592516.54      450643.327
#Sta/Elev= 30
    10.1  790.87    60.7  784.58   273.2  750.21   354.2  732.34     425  714.68
   475.6  700.69   526.2  681.98   546.4  678.41   586.9  677.77   647.6     670
   799.4  665.38  1032.1  665.99  1153.6  662.68  1598.3  658.12  1618.5     657
  1633.9   653.5  1648.9   651.6  1663.9  653.93  1689.3  657.78    1760   659.8
  1820.7  673.74  1901.5  714.14  2012.5  760.16  2082.9  786.49    2244  834.01
  2314.4  838.13  2354.7   837.5  2394.9  834.44  2525.7  818.84  2586.1  814.35
#Mann= 3 , 0 , 0
    10.1     .06       0  1633.9    .045       0  1663.9     .06       0
#XS Ineff= 2 , 0
          1361.6  675.85
Permanent Ineff=
       F       F
Bank Sta=1633.9,1663.9
XS Rating Curve= 0 ,0
Exp/Cntr=0.3,0.1

Type RM Length L Ch R = 1 ,91786.7 ,305,298.7,292.4
XS GIS Cut Line= 4
     1590285.452      450261.913     1591147.887      450258.356
     1591505.612      450721.268      1592300.23      451018.741
#Sta/Elev= 30
    10.1   806.6   152.2  781.67   233.4  763.92   365.3  714.87     487  681.72
   507.3  678.05   547.9  676.93   608.8  667.89   912.9  667.77   963.3  661.65
  1104.5  657.77  1225.6  657.99  1250.9  654.59  1265.9  651.21  1280.9  653.56
  1306.3  660.62  1326.4     663  1376.9  694.96  1447.5  722.45  1508.1  753.95
  1518.2  757.51  1528.3  757.93  1639.4  712.51  1780.8  677.95  1821.2  663.15
    1902  664.59  2033.3   673.4  2174.7  675.41  2225.2  670.92  2295.9  675.84
#Mann= 3 , 0 , 0
       0     .06       0  1250.9    .045       0  1280.9     .06       0
Bank Sta=1250.9,1280.9
XS Rating Curve= 0 ,0
Exp/Cntr=0.3,0.1

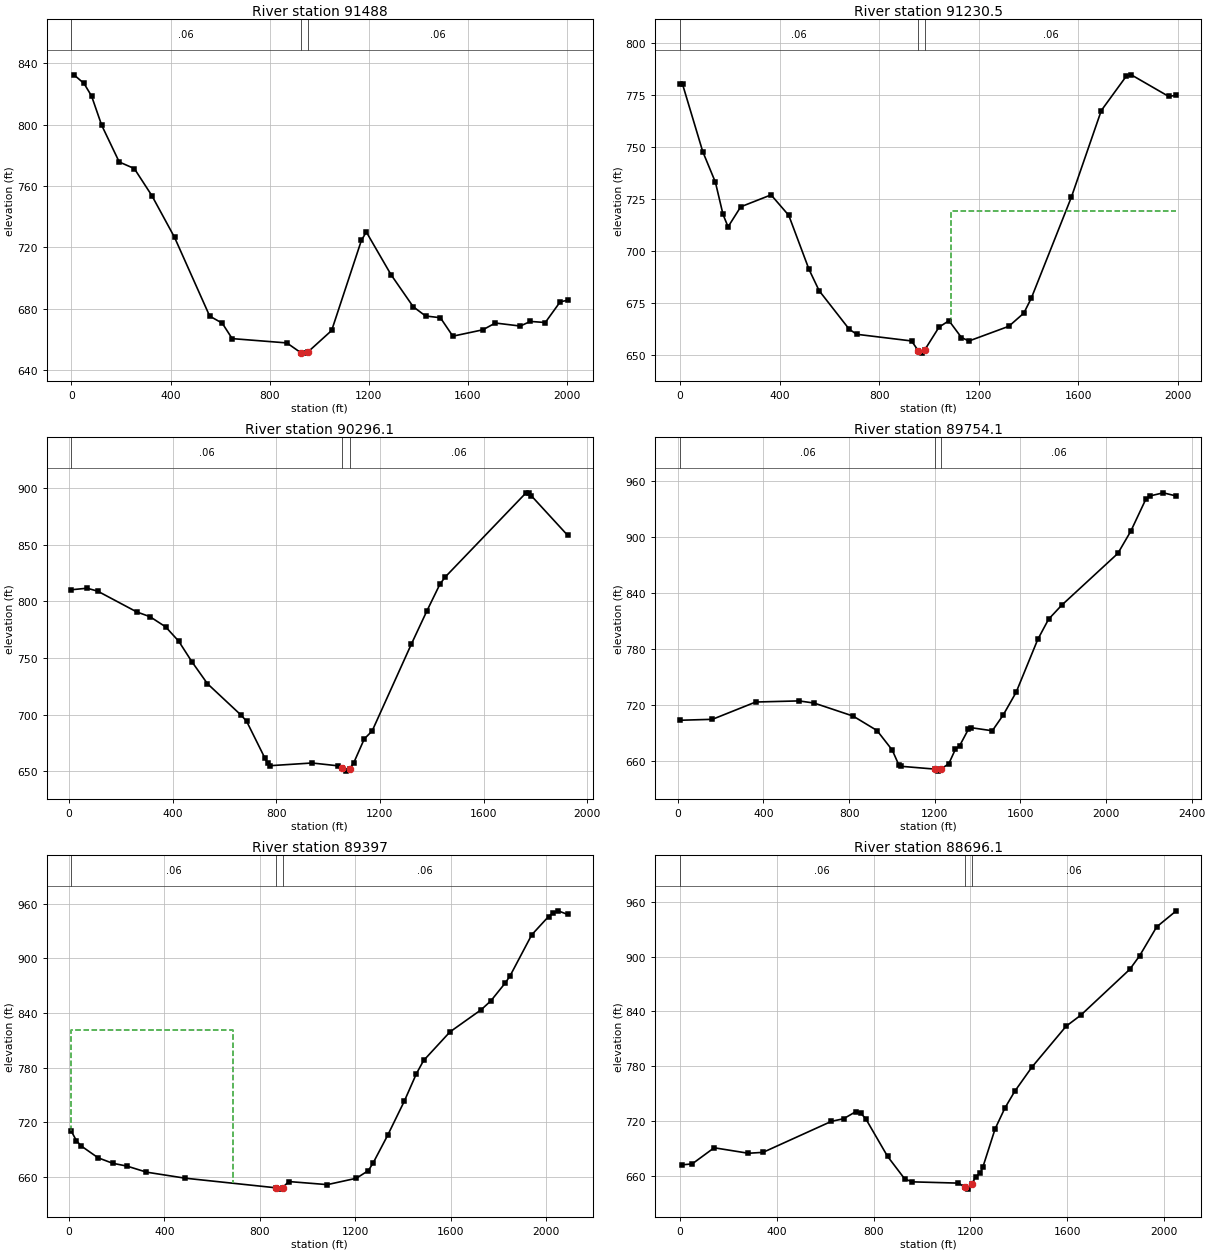
Type RM Length L Ch R = 1 ,91488   ,260.1,257.5,254.8
XS GIS Cut Line= 5
     1590341.493        450580.8     1590912.374      450724.491
     1591425.001      450868.182     1591793.397      450850.573
     1592261.893      451063.526
#Sta/Elev= 30
    10.1  832.42    50.7  826.78    81.2  818.56   121.8  799.62   192.8  775.62
   253.7  771.32   324.8  753.64   416.1  726.53   558.2  675.14   608.8  670.55
     649  660.47   869.9  657.66   925.3  651.41   940.3  651.01   955.3  651.81
  1050.8  665.76  1170.9  724.49  1190.8  729.97  1290.5  702.17  1380.2  681.26
  1430.1  675.22  1489.9  674.09  1540.3  662.06  1661.4  666.21  1711.9  670.64
  1812.8  668.66  1853.2  671.68  1913.7  670.96  1974.2  684.52  2004.5  685.43
#Mann= 3 , 0 , 0
       0     .06       0   925.3    .045       0   955.3     .06       0
Bank Sta=925.3,955.3
XS Rating Curve= 0 ,0
Exp/Cntr=0.3,0.1

Type RM Length L Ch R = 1 ,91230.5 ,931.6,934.4,937.8
XS GIS Cut Line= 4
     1590363.576      450745.922     1590887.218      451058.116
      1591547.54      451079.648     1592240.526      451284.028
#Sta/Elev= 30
       0  780.26    10.2  780.26    91.4  747.78   142.3  733.02   172.7  717.58
   193.1  711.52   243.9  721.17   365.8  726.92   436.9  717.05   518.2  691.02
   558.8  680.79   679.7  662.22   709.7  659.79     930  656.58   957.5  651.75
  970.06  650.72   982.5  652.21  1040.1  663.21  1080.1  666.34  1130.2  658.24
  1160.2  656.56  1320.5  663.65  1380.7  669.98  1410.8  677.19  1571.4  725.75
  1691.8  767.54  1792.1  784.08  1812.2  784.73  1962.7  774.31  1992.8  774.89
#Mann= 3 , 0 , 0
       0     .06       0   957.5    .045       0   982.5     .06       0
#XS Ineff= 2 , 0
                         1086.29          719.12
Permanent Ineff=
       F       F
Bank Sta=957.5,982.5
XS Rating Curve= 0 ,0
Exp/Cntr=0.3,0.1

Type RM Length L Ch R = 1 ,90296.1 ,534.3,541.9,549.3
XS GIS Cut Line= 3
     1590306.984      451690.219     1591361.892      451865.337
     1592201.822      452027.557
#Sta/Elev= 30
    10.1  810.36    70.6  811.69     111  809.12   262.3   790.7   312.7  786.57
   373.3  777.57   423.7  764.93   474.1  746.93   534.7  727.32   665.8  699.26
     686  694.02   756.6  661.45   766.7  657.23   776.8   654.9   938.2  657.28
  1039.1  654.77  1054.3  652.49 1069.67  650.09  1084.3  652.21  1099.5  657.65
  1139.8  678.59    1170  685.54  1320.9  762.11  1381.3  791.65  1431.7  815.33
  1451.8  821.56  1763.8  895.98  1773.8  895.54  1783.9  893.45  1924.8  858.31
#Mann= 3 , 0 , 0
    10.1     .06       0  1054.3    .045       0  1084.3     .06       0
Bank Sta=1054.3,1084.3
XS Rating Curve= 0 ,0
Exp/Cntr=0.3,0.1

Type RM Length L Ch R = 1 ,89754.1 ,365.2,357.1,349
XS GIS Cut Line= 4
     1589976.823      451927.074     1590795.048      451948.606
     1591189.806       452465.38      1592044.08      452555.819
#Sta/Elev= 30
    10.1  703.59   161.7   704.6   363.8  723.15   565.9  724.34   636.6  722.04
   818.5  708.09   930.3  692.58  1001.4  671.66  1031.9  655.81    1042  654.23
  1199.8  651.22  1214.8  649.04  1229.8  651.36  1265.6  656.99  1296.1  672.34
  1316.4  676.33    1357  693.91  1367.2  695.71  1468.8  692.31  1519.3  709.08
    1580  733.54    1681  790.22  1731.6  811.95  1792.2  826.82    2055  882.48
  2115.6  906.35  2186.4  940.95  2206.6   944.2  2267.2  947.47  2327.9  944.08
#Mann= 3 , 0 , 0
    10.1     .06       0  1199.8    .045       0  1229.8     .06       0
Bank Sta=1199.8,1229.8
XS Rating Curve= 0 ,0
Exp/Cntr=0.3,0.1

Type RM Length L Ch R = 1 ,89397   ,702.6,701,701.4
XS GIS Cut Line= 4
     1590003.625       452318.95     1590449.325      452514.135
     1591292.506      452611.229     1592046.368      452660.702
#Sta/Elev= 30
    10.1  709.91    30.4  700.02    50.7  694.05   121.6  681.05   182.5  675.05
   243.3   671.9   324.4   665.3   486.6  658.67   865.6  648.16   880.6  646.66
   895.6   648.4  920.99  654.98  1082.7   651.6    1204  658.55  1254.5  666.92
  1274.7  675.35  1335.3  705.52  1405.8  743.36  1456.2  773.38  1486.4  787.82
  1597.2  819.26  1728.2  843.62  1768.5  853.31  1828.9  872.94    1849  880.75
  1939.7  925.73  2010.2  945.79  2030.4  950.12  2050.5  952.05  2090.8  948.02
#Mann= 3 , 0 , 0
    10.1     .06       0   865.6    .045       0   895.6     .06       0
#XS Ineff= 2 , 0
          688.45  821.25
Permanent Ineff=
       F       F
Bank Sta=865.6,895.6
XS Rating Curve= 0 ,0
Exp/Cntr=0.3,0.1

Type RM Length L Ch R = 1 ,88696.1 ,917.2,924.1,929
XS GIS Cut Line= 3
     1590030.444      453026.252     1591220.967      452988.218
     1592069.318      453128.281
#Sta/Elev= 30
    10.1  672.31    50.5   673.3   141.3  690.95   282.6  684.94   343.2  685.93
   625.8  719.84   676.3   722.7   726.8  730.46     747  728.67   767.2  722.93
     858   681.5   928.7  656.91     959  653.68  1150.8  652.28  1176.1  648.15
  1191.1  645.71  1206.1  650.83  1221.5  659.11  1241.7  663.52  1251.8  669.85
  1302.4  711.64  1342.9  734.44  1383.3  752.62  1454.1  779.05  1595.8  823.88
  1656.5  835.97  1858.8  886.07  1899.2  900.77    1970  932.52    2051   950.1
#Mann= 3 , 0 , 0
       0     .06       0  1176.1    .045       0  1206.1     .06       0
Bank Sta=1176.1,1206.1
XS Rating Curve= 0 ,0
Exp/Cntr=0.3,0.1

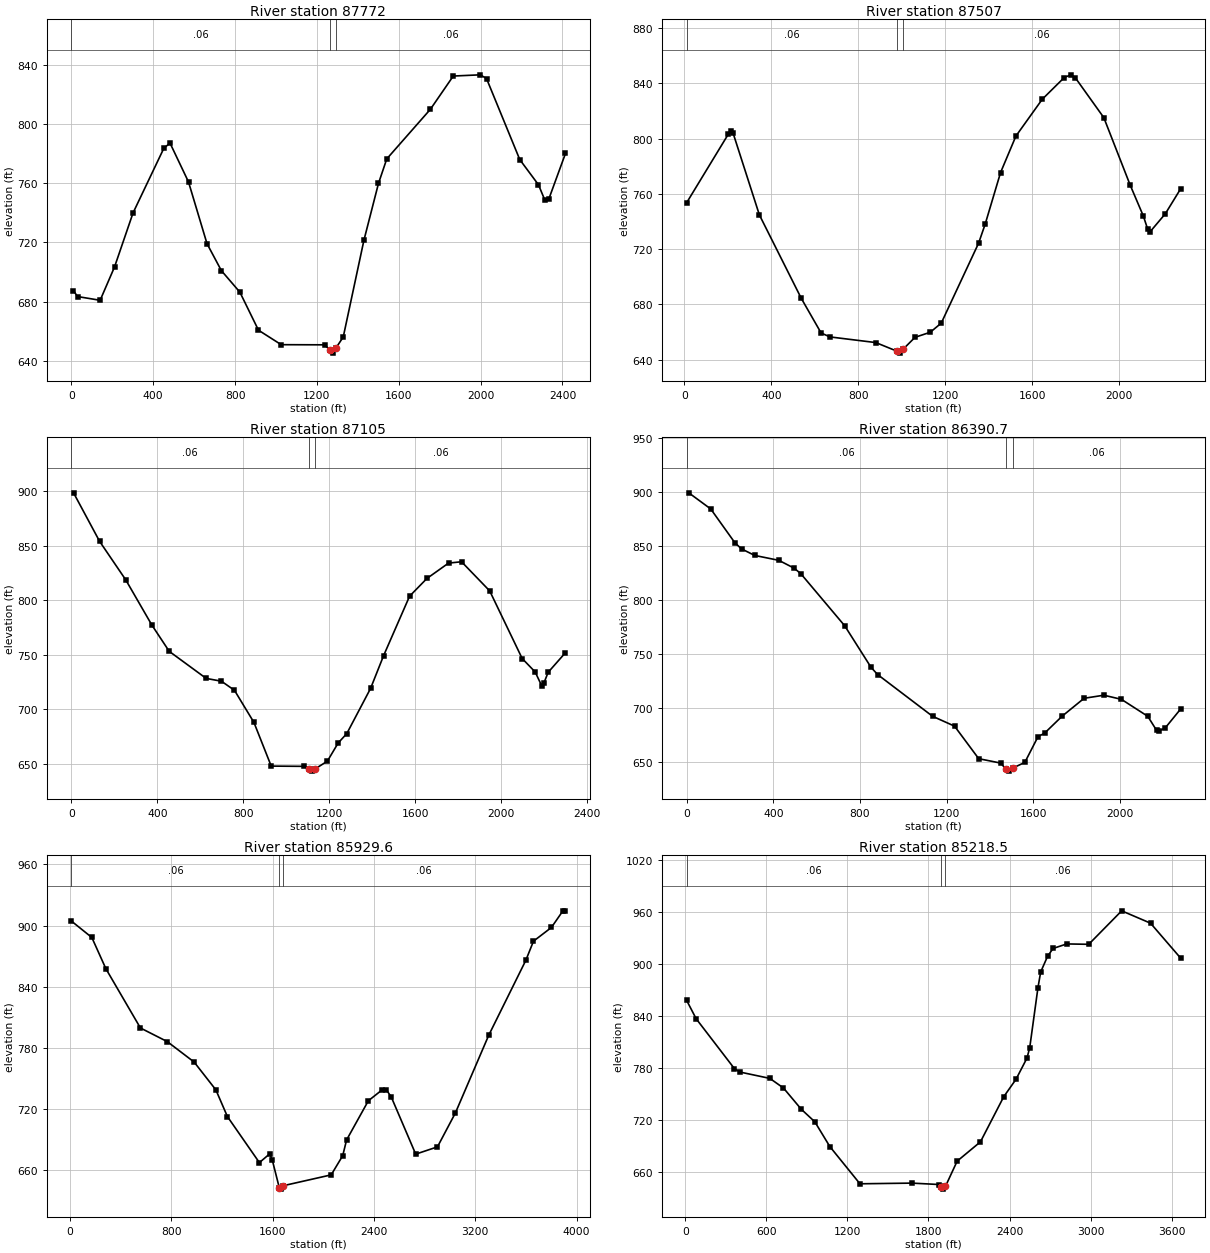
Type RM Length L Ch R = 1 ,87772   ,267.4,265,262.6
XS GIS Cut Line= 4
      1589596.42      453262.073     1590393.113      453470.218
     1590889.072      453852.949     1591853.891      453854.451
#Sta/Elev= 30
      10  687.48    30.1  683.44   140.6  680.92   210.9  703.44   301.3  739.94
   451.9  783.65     482  787.17   572.4  760.91   662.8  719.19   733.1  700.94
   823.4  686.42   914.4   660.7  1025.5  650.92  1237.7  650.82  1263.1  647.38
  1278.1  645.21  1293.1  648.72  1328.6   656.1  1429.7  721.51  1500.7  759.85
  1541.3  776.47  1754.6  810.02  1866.3  832.46  1998.3  833.28  2028.8  830.77
  2191.3     776  2282.7  758.98  2313.2   748.8  2333.5  749.44  2414.7  780.19
#Mann= 3 , 0 , 0
       0     .06       0  1263.1    .045       0  1293.1     .06       0
Bank Sta=1263.1,1293.1
XS Rating Curve= 0 ,0
Exp/Cntr=0.3,0.1

Type RM Length L Ch R = 1 ,87507   ,415.5,402,388.5
XS GIS Cut Line= 4
      1589657.99      453495.663      1590316.46      453812.124
     1590691.012      453981.106     1591832.773      453946.154
#Sta/Elev= 30
    10.1  753.47   202.9  803.41   213.1  805.41   223.2  804.39     345  744.74
   537.8   684.3   629.1  659.21   669.7  656.36   880.9  652.26   976.1  646.16
   991.1  644.62  1006.1  647.41  1061.3  656.08  1131.5  659.75  1181.9  666.35
  1353.8  724.26  1384.1  738.06  1454.8  775.37  1525.6  801.84  1646.9  828.51
    1748  844.22  1778.3  846.17  1798.5  844.12    1930  815.16  2051.3   766.3
  2111.9   743.9  2132.1  734.27  2142.2  732.37    2213  745.55  2283.8  763.71
#Mann= 3 , 0 , 0
    10.1     .06       0   976.1    .045       0  1006.1     .06       0
Bank Sta=976.1,1006.1
XS Rating Curve= 0 ,0
Exp/Cntr=0.3,0.1

Type RM Length L Ch R = 1 ,87105   ,711.6,714.2,716.9
XS GIS Cut Line= 4
     1589755.872      454376.995     1590529.484      454467.878
        1590874.      454022.879     1591830.874       454010.17
#Sta/Elev= 30
    10.1   898.4   131.5  853.82   252.9  818.56   374.3   777.1   455.2  752.94
   627.2  728.09     698  725.53   758.7  717.19   849.3   687.7   929.7  647.63
  1080.4   647.4  1105.6  644.81  1120.6  643.01  1135.6  645.24    1191  652.17
  1241.2  668.84  1281.4  677.48  1392.1  718.99  1452.5  748.97  1573.4  803.55
    1654   819.8  1754.7  833.92  1815.2  835.14  1946.1   808.4  2097.2  746.36
  2157.6  734.01  2187.9  721.38  2197.9  723.66  2218.1  733.71  2298.7  751.74
#Mann= 3 , 0 , 0
       0     .06       0  1105.6    .045       0  1135.6     .06       0
Bank Sta=1105.6,1135.6
XS Rating Curve= 0 ,0
Exp/Cntr=0.3,0.1

Type RM Length L Ch R = 1 ,86390.7 ,460.2,461.1,462.6
XS GIS Cut Line= 3
     1589799.628      454537.906     1590988.839      454876.991
     1591814.241      454238.201
#Sta/Elev= 30
    10.1  899.11   111.5  884.14     223  852.81   253.4  847.17   314.2   841.1
   425.7  836.55   496.7  829.24   527.1  824.18   729.8  775.87   851.4  737.34
   881.8  730.67  1135.2  692.03  1236.6  682.89  1348.1  652.74  1449.4  648.67
  1474.9  642.77  1489.9  641.21  1504.9  644.04  1560.9  649.28  1621.7  673.12
  1652.1   676.4  1733.1  692.13  1834.5  708.72  1925.7  711.56  2006.7  707.73
  2128.3  692.02  2168.9     679    2179  678.21  2209.4  681.38  2280.3  698.85
#Mann= 3 , 0 , 0
       0     .06       0  1474.9    .045       0  1504.9     .06       0
Bank Sta=1474.9,1504.9
XS Rating Curve= 0 ,0
Exp/Cntr=0.3,0.1

Type RM Length L Ch R = 1 ,85929.6 ,700.5,711.1,721.7
XS GIS Cut Line= 4
     1589861.951      454652.647     1591265.169      455168.573
     1591878.838      454833.926     1593463.252      455500.529
#Sta/Elev= 30
    10.1  904.41   171.7  888.26   282.8  857.56   555.6  799.39   767.7  786.01
   979.9  765.92  1151.6  738.61  1242.5  712.42  1495.1  667.22  1576.1  675.75
  1596.4  670.08  1652.3   642.6 1667.02  641.17  1682.3  644.48  2062.3  655.17
  2153.5  674.04  2183.9  689.45  2355.8  727.92    2467  738.88  2497.4  738.89
  2537.8  731.36  2729.9  675.52  2901.8  682.68  3043.4  715.98  3306.3  792.15
  3599.5  865.78  3660.2  884.63  3801.7  898.08  3892.8  914.43    3913  913.93
#Mann= 3 , 0 , 0
    10.1     .06       0  1652.3    .045       0  1682.3     .06       0
Bank Sta=1652.3,1682.3
XS Rating Curve= 0 ,0
Exp/Cntr=0.3,0.1

Type RM Length L Ch R = 1 ,85218.5 ,974.8,985.2,995.7
XS GIS Cut Line= 4
     1590018.093      454809.703     1591148.536      455186.517
     1592350.753      455958.089     1592745.511       456927.04
#Sta/Elev= 30
    10.1  858.26    80.8  837.01   363.5  779.64   403.9  775.64   626.1   768.3
   727.1   757.2   858.3  732.84   959.3  718.22  1070.4   689.7  1292.9  646.89
  1677.9  647.67  1880.5  646.03  1895.9  642.96 1910.52  640.74  1925.9  644.02
  2012.2  672.99  2184.5  695.22  2356.7  747.14  2447.9  767.34  2528.9  791.74
  2549.2   803.7    2610  872.75  2630.3  890.88  2681.1  908.89  2721.7  917.96
  2823.3  923.19  2985.8  922.75  3229.6  961.32  3442.9   947.1  3666.4  906.76
#Mann= 3 , 0 , 0
    10.1     .06       0  1895.9    .045       0  1925.9     .06       0
Bank Sta=1895.9,1925.9
XS Rating Curve= 0 ,0
Exp/Cntr=0.3,0.1

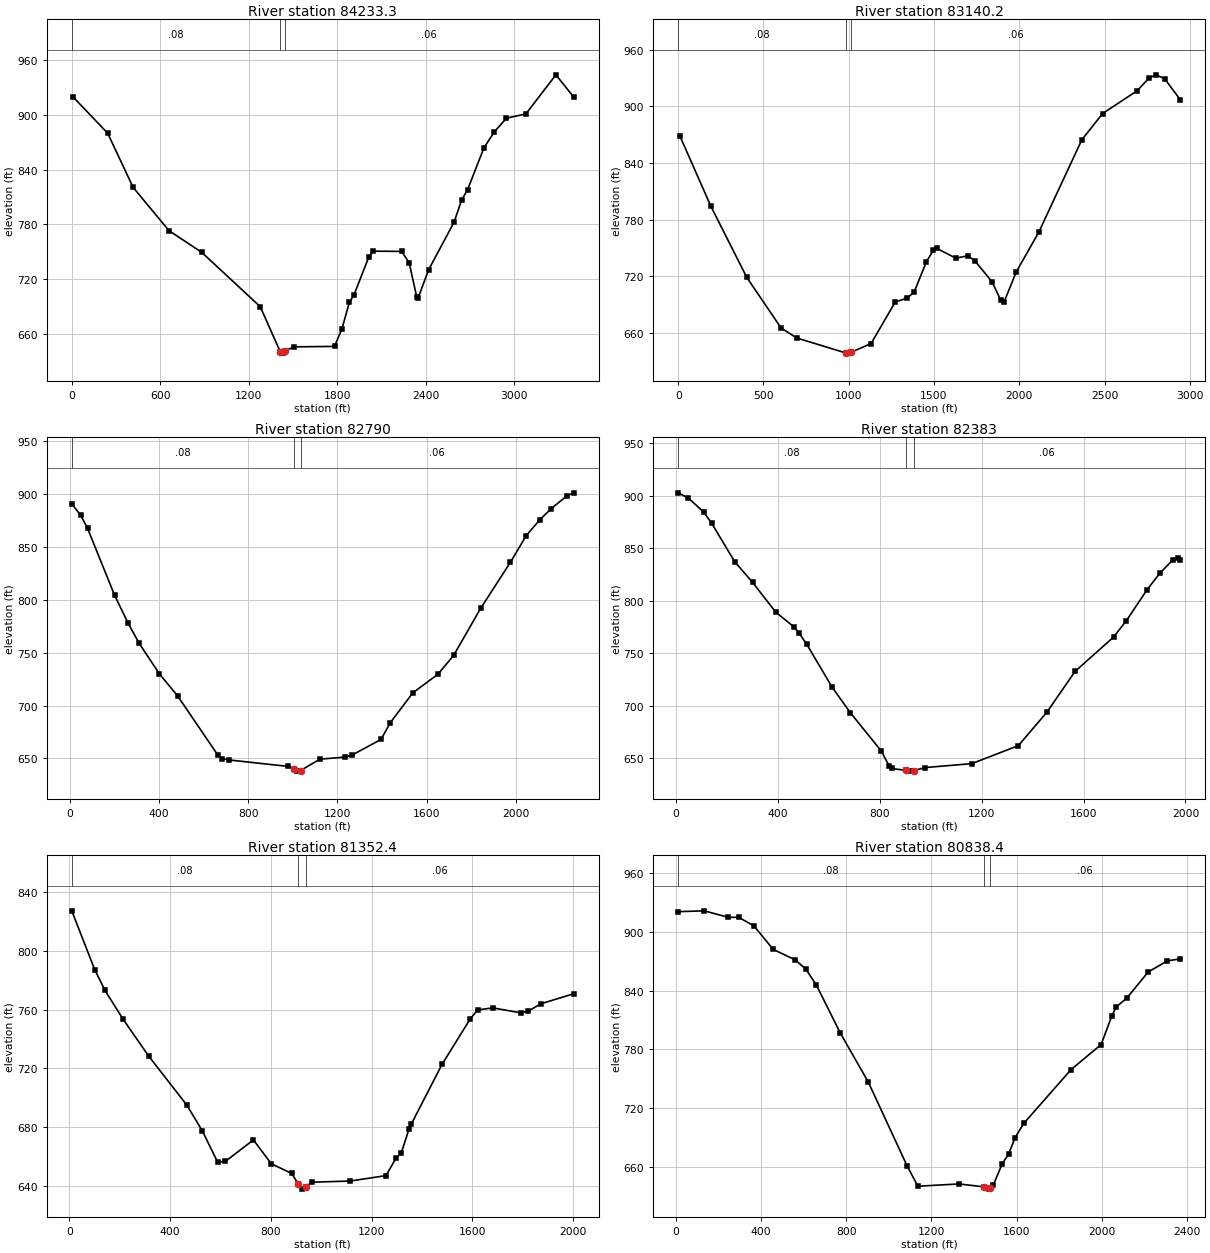
Type RM Length L Ch R = 1 ,84233.3 ,1106.1,1093.1,1081.4
XS GIS Cut Line= 4
     1589698.755      454745.154     1590897.326      455186.517
     1590834.524      455868.371     1591641.983      457061.616
#Sta/Elev= 30
    10.1  918.95   243.3  879.63   415.6  820.54   658.9   773.3   881.9  749.47
  1277.3  690.29  1413.3  641.04  1428.3  639.64  1443.3  642.23  1508.9   646.5
  1780.7  646.98  1831.1   666.1  1881.4  695.11  1911.6  702.78  2012.7  744.27
  2043.2   750.9  2235.9  750.64  2286.7  738.19  2337.4   701.3  2347.6   699.9
  2418.6  730.65  2591.1  782.55  2641.8  806.46  2682.4  817.98    2794  863.82
    2865  881.31  2946.2  895.98  3078.1  900.68    3281   943.3  3402.8  918.86
#Mann= 3 , 0 , 0
       0     .08       0  1413.3    .045       0  1443.3     .06       0
Bank Sta=1413.3,1443.3
XS Rating Curve= 0 ,0
Exp/Cntr=0.3,0.1

Type RM Length L Ch R = 1 ,83140.2 ,348,350.2,351.1
XS GIS Cut Line= 4
     1589306.897      455658.249     1589820.714      455563.331
     1590655.089      455778.653     1591516.378       457079.56
#Sta/Elev= 30
      10  868.62   190.9  794.24   401.9  718.57   603.6  664.75   694.9  654.24
     984  638.25     999  638.15    1014   639.1  1130.8  648.29  1272.7  692.43
  1343.7  696.64  1384.2  703.27  1455.1  735.06  1495.7  747.13  1515.9  749.41
  1627.4  739.03  1698.3   741.4  1738.8  736.32  1840.1  713.94  1890.8  694.54
    1911  692.48    1982  724.32  2113.7  766.28  2366.9  864.62  2488.5   892.5
  2691.1  916.65    2762  930.39  2802.6   933.6  2853.2  929.32  2944.4  907.09
#Mann= 3 , 0 , 0
       0     .08       0     984    .045       0    1014     .06       0
Bank Sta=984,1014
XS Rating Curve= 0 ,0
Exp/Cntr=0.3,0.1

Type RM Length L Ch R = 1 ,82790   ,409.4,407,404.6
XS GIS Cut Line= 4
     1589281.287       455740.35      1589964.79      455868.507
     1590423.048      456109.286     1591157.037      456854.926
#Sta/Elev= 30
    10.1  890.81    50.4  879.72    80.6  867.62   201.6  804.45     262  778.09
   312.4  758.71   403.1  729.89   483.8  709.26   665.2  653.01   685.3  649.89
   715.7  648.59   979.6  642.52  1005.2  639.77 1020.19  638.06  1035.2  638.65
  1121.7  649.36  1233.4  651.31  1263.9  653.01  1395.9  668.06  1436.6  683.72
  1538.1  712.08  1649.9   729.5    1721  747.47  1842.9   792.3  1974.9  835.32
    2046  860.71    2107  875.63  2157.8  886.18  2228.9  898.31  2259.4  901.11
#Mann= 3 , 0 , 0
    10.1     .08       0  1005.2    .045       0  1035.2     .06       0
Bank Sta=1005.2,1035.2
XS Rating Curve= 0 ,0
Exp/Cntr=0.3,0.1

Type RM Length L Ch R = 1 ,82383   ,1026.2,1030.6,1035
XS GIS Cut Line= 4
     1589181.669      455879.018     1589722.025      456191.355
     1590520.512      456424.621     1590757.852      456891.613
#Sta/Elev= 30
    10.1  902.69    50.3  897.66   110.7   884.1   140.9  873.87   231.5  837.18
     302  817.38   392.6  789.16   463.1   775.3   483.2  769.57   513.4   758.9
   614.1  717.57     685  693.53   806.7  656.95   837.2  642.88   847.3   640.4
   903.3  638.52  917.77  637.84   933.3  638.37   979.2  641.24  1161.8  644.97
  1344.4   662.1    1456   693.8  1566.8  732.72  1717.9  765.42  1768.3  781.05
  1848.9  810.28  1899.2  826.17  1949.6  838.62  1969.8  840.43  1979.8  839.15
#Mann= 3 , 0 , 0
    10.1     .08       0   903.3    .045       0   933.3     .06       0
Bank Sta=903.3,933.3
XS Rating Curve= 0 ,0
Exp/Cntr=0.3,0.1

Type RM Length L Ch R = 1 ,81352.4 ,515.3,514,512.6
XS GIS Cut Line= 4
     1589004.448      456143.402     1589282.408      456819.379
     1589973.234      457330.769     1590343.934      457509.749
#Sta/Elev= 30
    10.2  827.34   101.5  787.18   142.1  773.12   213.2  753.63   314.7  728.53
     467   694.9   527.9  677.51   588.8  656.18   619.2  656.61   730.9  671.26
   801.7  655.04   882.6  648.42     908  641.57   923.2  637.74     938  639.48
   963.5  642.45  1115.1  643.27  1256.7  646.93  1297.2  658.99  1317.4  662.36
  1347.7  678.39  1357.8  682.26  1479.2  722.74  1590.4  753.55  1620.5  759.85
  1680.8  761.22  1791.2  757.85  1821.3  759.04  1871.5  764.02  2002.1  770.87
#Mann= 3 , 0 , 0
    10.2     .08       0     908    .045       0     938     .06       0
Bank Sta=908,938
XS Rating Curve= 0 ,0
Exp/Cntr=0.3,0.1

Type RM Length L Ch R = 1 ,80838.4 ,157.6,156.2,154.8
XS GIS Cut Line= 3
      1588125.05      456693.774     1589704.081      457590.951
     1590231.135      457758.971
#Sta/Elev= 30
    10.1  920.65   131.9   921.5   243.5  914.97   294.2  914.82   365.3  906.24
   456.6  882.04     558  871.61   608.8  862.23   659.5  845.52   771.1  796.84
     903  746.59  1085.6   660.8  1136.3  640.08  1329.1   642.4    1446  639.47
 1471.15  637.11    1476  638.53  1491.4   641.7    1532  662.73  1562.5  673.03
  1592.9  689.63  1633.5  704.24  1856.3  759.33  1997.2  784.86  2047.4   814.1
  2067.6  823.17  2117.9  832.34  2218.4  859.03    2309  870.43  2369.3  872.38
#Mann= 3 , 0 , 0
    10.1     .08       0    1446    .045       0    1476     .06       0
Bank Sta=1446,1476
XS Rating Curve= 0 ,0
Exp/Cntr=0.3,0.1