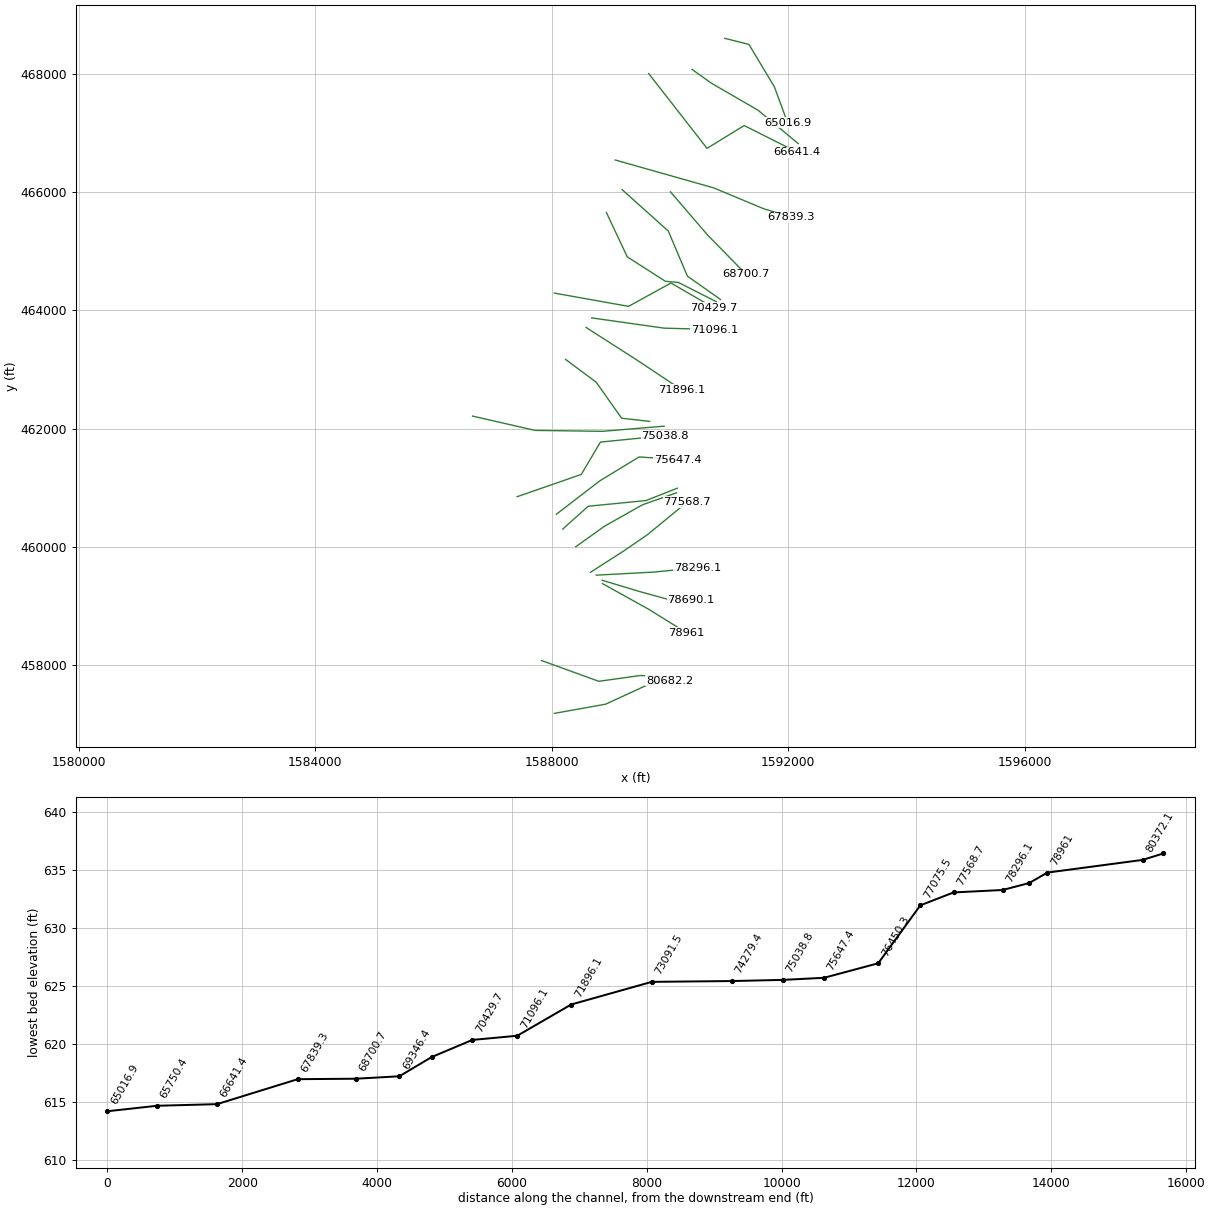
HEC-RAS study BEECHFK.prj: BEECHFK

--- BEECHFK.g01 (geometry) --- (continued)

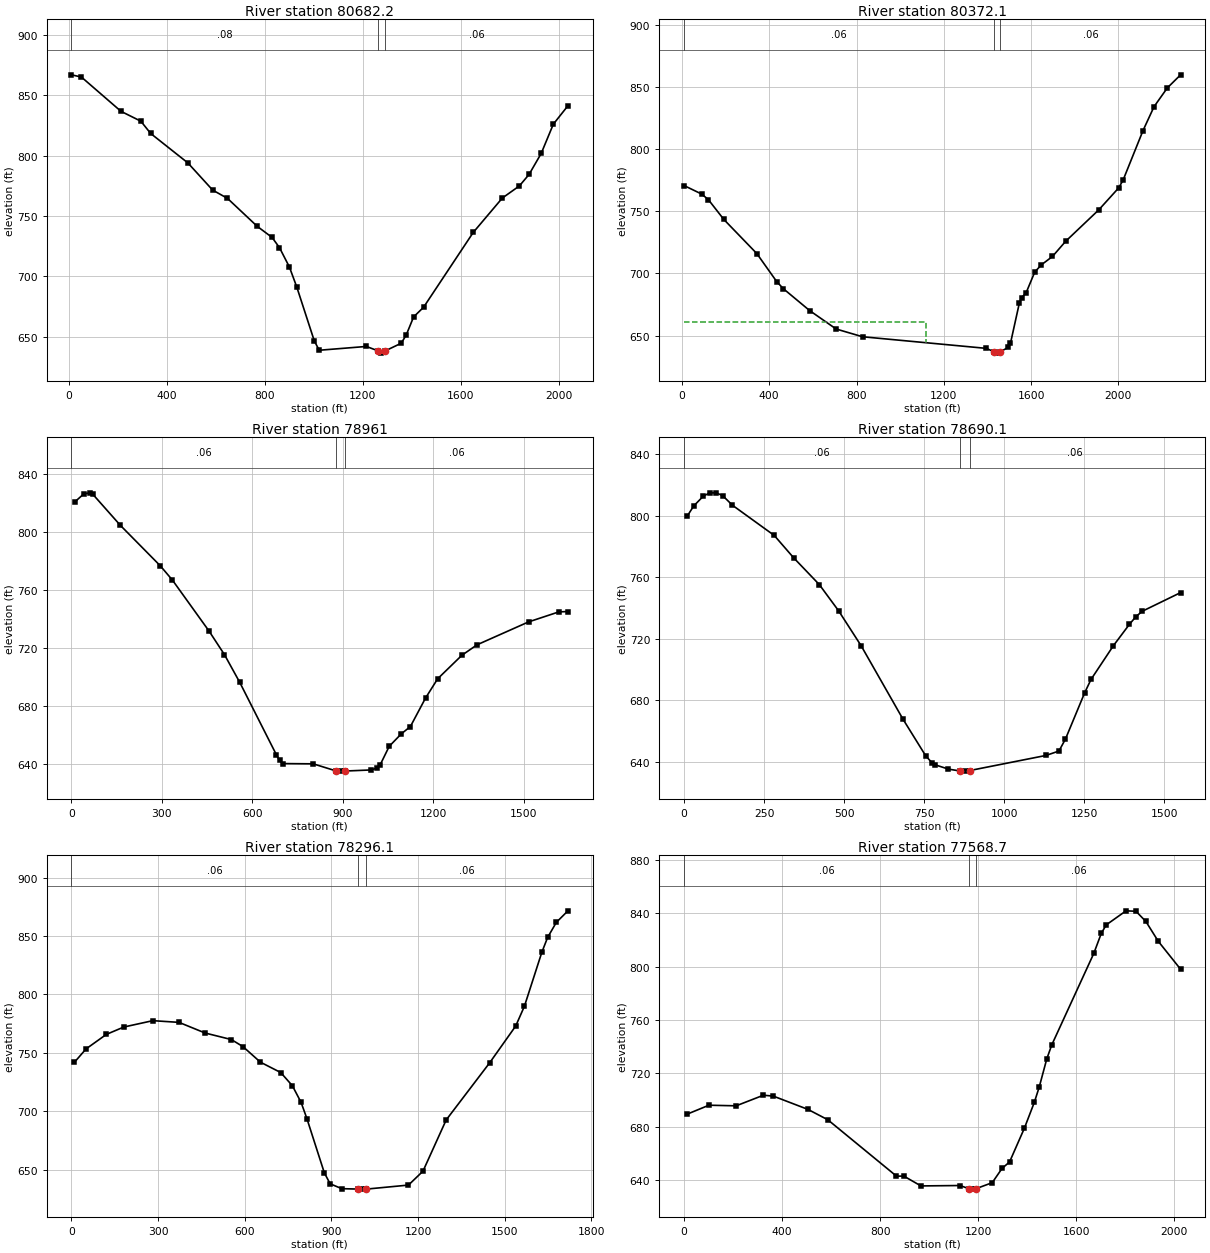
Type RM Length L Ch R = 1 ,80682.2 ,311.8,310,308.2
XS GIS Cut Line= 4
     1588046.321      457181.143      1588912.35      457336.485
      1589603.62      457654.935     1589991.975       457736.49
#Sta/Elev= 30
    10.1  866.97    50.6  865.13   212.4  836.72   293.3  828.57   333.7  818.37
   485.4  794.01   586.6  771.51   647.2  764.63   768.6  741.49   829.3  732.29
   859.6  723.83   900.1  707.81   930.6  691.02  1001.6  646.71  1021.9  638.81
  1214.7  641.96  1260.6  638.44 1275.61  636.43  1290.6   638.2  1356.8  644.62
  1377.1  651.32  1407.5  666.43  1448.1  674.39  1650.9  736.37  1769.9  764.91
  1839.4  774.92    1879  784.44  1928.6  801.83  1978.2  826.09  2037.8  841.33
#Mann= 3 , 0 , 0
    10.1     .08       0  1260.6    .045       0  1290.6     .06       0
Bank Sta=1260.6,1290.6
XS Rating Curve= 0 ,0
Exp/Cntr=0.3,0.1

Type RM Length L Ch R = 1 ,80372.1 ,1418.5,1411.1,1403.3
XS GIS Cut Line= 4
     1587828.982      458075.426     1588796.648      457723.716
     1589498.765      457821.928     1590045.008      457797.301
#Sta/Elev= 30
    10.1  770.58    90.8  763.73   121.1  759.28   191.8  743.39   343.2  715.91
     434  693.46   464.3  687.73   585.5  670.05   706.6  655.27   827.7  649.03
  1394.2  639.71  1429.8  637.02  1444.8  635.87  1459.8  637.06  1495.5  640.49
  1505.6   643.7  1546.1  675.92  1556.3  680.49  1576.5  684.03    1617  701.09
  1647.4  706.88    1698  713.57  1758.8  725.83  1910.7  751.13  2001.8  768.76
  2022.1  775.11  2113.2  814.85  2163.8  834.07  2224.6  849.14  2285.4  859.65
#Mann= 3 , 0 , 0
    10.1     .06       0  1429.8    .045       0  1459.8     .06       0
#XS Ineff= 2 , 0
         1116.33  661.15
Permanent Ineff=
       F       F
Bank Sta=1429.8,1459.8
XS Rating Curve= 0 ,0
Exp/Cntr=0.3,0.1

Type RM Length L Ch R = 1 ,78961   ,268.2,270.9,274
XS GIS Cut Line= 3
     1588860.735      459376.332     1589641.525      458942.752
     1590281.217      458544.453
#Sta/Elev= 30
    10.1  820.66    40.6  826.34    60.9  827.11      71  826.06   162.4  804.58
   294.3  776.73   334.9  766.78   456.7  731.45   507.4  715.29   558.2   696.1
     680  645.95   690.1  642.24   700.3     640   801.8  639.82   878.1  634.88
   893.1  634.78   908.1  634.85   993.6  635.59  1013.7  636.94  1023.7  639.03
  1053.9  651.92    1094  660.54  1124.2   665.6  1174.4  685.28  1214.6  698.59
    1295  714.85  1345.2  722.07    1516  737.89  1616.5  744.82  1646.7  745.08
#Mann= 3 , 0 , 0
       0     .06       0   878.1    .045       0   908.1     .06       0
Bank Sta=878.1,908.1
XS Rating Curve= 0 ,0
Exp/Cntr=0.3,0.1

Type RM Length L Ch R = 1 ,78690.1 ,390.4,394.1,398.4
XS GIS Cut Line= 4
     1588854.097      459433.597     1589498.765       459239.42
     1590007.509      459099.612     1590357.027      459095.729
#Sta/Elev= 30
      10   799.9    30.1  806.42    60.3  812.83    80.4   814.9   100.5  814.88
   120.6  813.01   150.7  806.84   281.4  787.17   341.7   772.7   422.1  755.21
   482.3  738.18   552.7  715.43   683.4  667.67   754.4  643.83   774.7  639.15
   784.9  637.92   825.5  635.17   861.2     634   876.2  633.88   891.2  634.23
  1129.9  644.08  1170.4  646.94  1190.7  654.67  1250.8  684.84  1270.8  693.58
  1340.7  715.52  1390.6  729.36  1410.6  734.32  1430.6  737.86  1550.4     750
#Mann= 3 , 0 , 0
       0     .06       0   861.2    .045       0   891.2     .06       0
Bank Sta=861.2,891.2
XS Rating Curve= 0 ,0
Exp/Cntr=0.3,0.1

Type RM Length L Ch R = 1 ,78296.1 ,721.4,727.4,732.7
XS GIS Cut Line= 3
     1588753.074      459519.881     1589727.739      459571.779
     1590466.682      459645.485
#Sta/Elev= 30
    10.1  741.85    50.3   753.3   120.7  765.75   181.1  772.05   281.7  777.51
   372.3  776.04   462.9  766.91   553.4  761.34   593.7  755.29   654.1  741.97
   724.5  733.09   764.7  721.79   794.9  707.53     815  693.68   875.4  647.22
   895.5  637.84   935.8  633.68   991.2  633.32  1006.2  633.28  1021.2  633.31
  1166.7  636.75  1216.9  648.66  1297.2  692.51  1447.7  741.41    1538  772.95
  1568.1  789.87  1628.3     836  1648.4  848.75  1678.5  861.63  1718.7  871.54
#Mann= 3 , 0 , 0
       0     .06       0   991.2    .045       0  1021.2     .06       0
Bank Sta=991.2,1021.2
XS Rating Curve= 0 ,0
Exp/Cntr=0.3,0.1

Type RM Length L Ch R = 1 ,77568.7 ,495.8,493.2,491.2
XS GIS Cut Line= 4
     1588657.059      459568.758     1589218.659      459928.824
     1589621.583      460206.042     1590294.207       460758.05
#Sta/Elev= 30
    10.1  689.18   101.1  696.05   212.3   695.6   323.4  703.55   363.9  702.89
   505.4   692.9   586.3  685.14   866.7  642.81   896.7  642.85   966.5  635.47
  1126.2  635.78  1161.4  633.43  1176.4  633.07  1191.4  633.43  1257.4   637.9
  1297.8  648.68  1328.2  653.47  1388.9  678.89  1429.4  698.27  1449.6  709.91
    1480  730.75  1500.2  741.21  1672.2  810.07  1702.6  825.04  1722.8  831.41
  1803.7  841.96  1844.2  841.62  1884.7  833.95  1935.3  819.06  2026.3   798.1
#Mann= 3 , 0 , 0
       0     .06       0  1161.4    .045       0  1191.4     .06       0
Bank Sta=1161.4,1191.4
XS Rating Curve= 0 ,0
Exp/Cntr=0.3,0.1

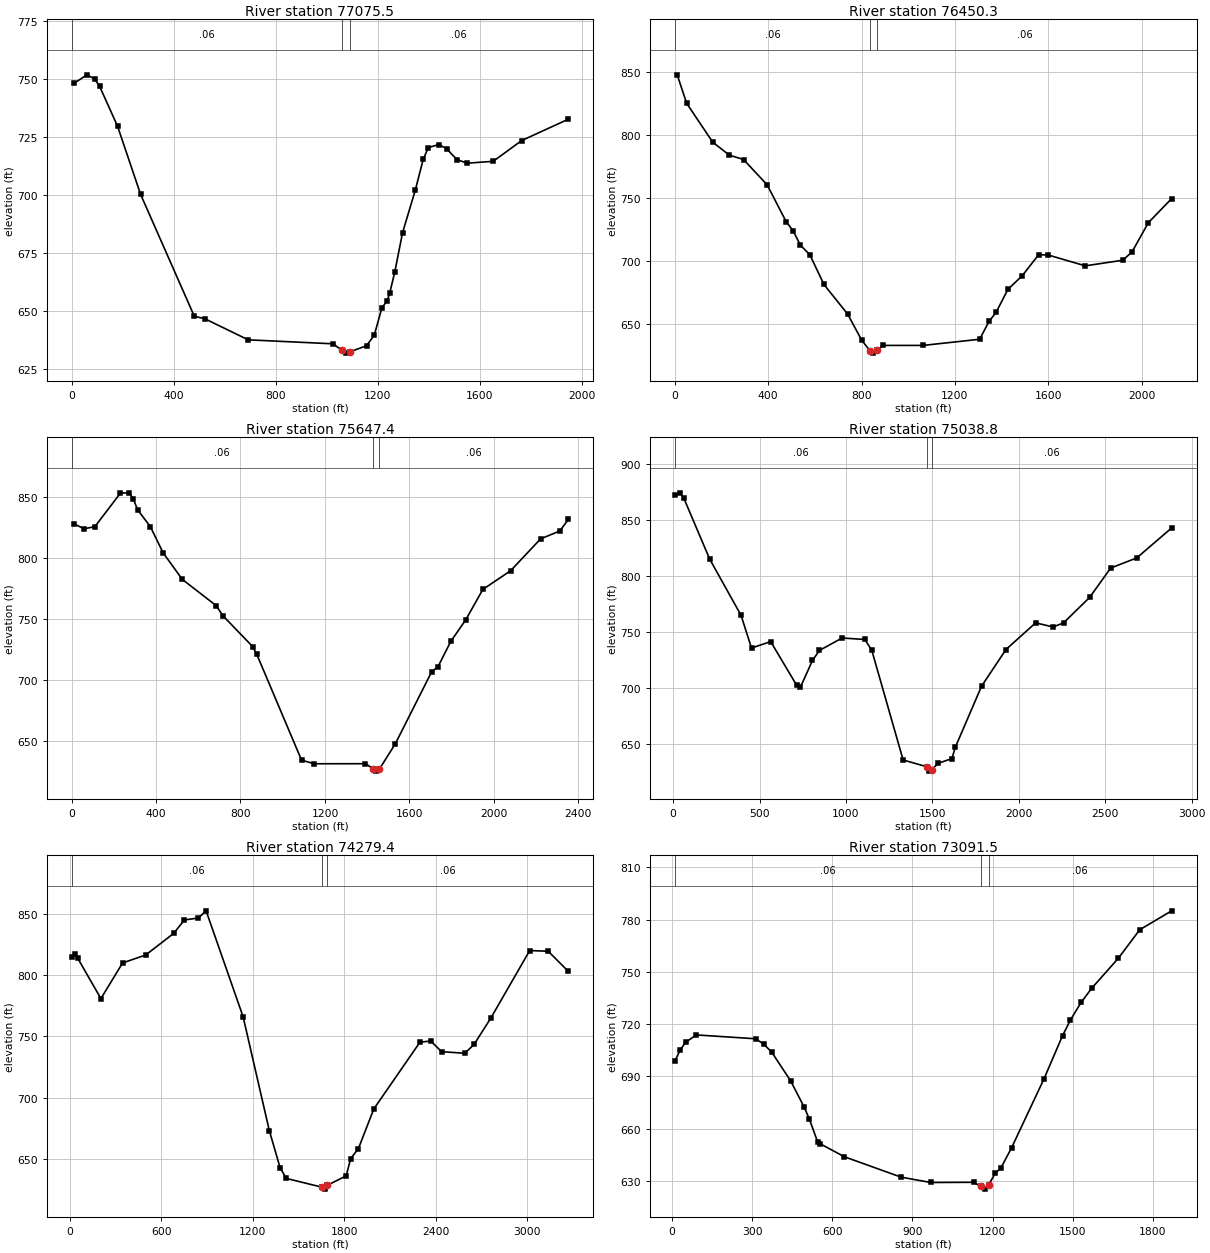
Type RM Length L Ch R = 1 ,77075.5 ,630,625.2,619.7
XS GIS Cut Line= 4
      1588407.49      460000.594     1588896.816      460350.113
       1589537.6      460711.282     1590112.364      460913.226
#Sta/Elev= 30
      10   748.2    60.1  751.89    90.2  750.16   110.2   746.9   180.4  729.73
   270.6  700.38   481.1  647.83   521.2  646.83     692  637.69  1024.5  635.98
  1059.9  633.12  1074.9  631.96  1089.9   632.5  1155.5  635.14  1185.8  639.64
    1216  651.55  1236.1  654.45  1246.2  657.68  1266.4  666.99  1296.6  683.81
    1347  702.33  1377.5  715.43  1397.8  720.55  1438.4  721.83  1468.9   720.1
  1509.5  715.36  1550.1  713.82  1651.7  714.61  1763.3  723.56  1946.1  732.77
#Mann= 3 , 0 , 0
       0     .06       0  1059.9    .045       0  1089.9     .06       0
Bank Sta=1059.9,1089.9
XS Rating Curve= 0 ,0
Exp/Cntr=0.3,0.1

Type RM Length L Ch R = 1 ,76450.3 ,797.9,802.9,807.8
XS GIS Cut Line= 4
     1588187.853      460300.425     1588618.497      460686.211
     1589594.017      460782.028     1590124.464      460991.048
#Sta/Elev= 30
    10.1  847.61    50.7  825.01   162.3  794.21   233.3  783.96   294.2  780.48
   395.6  760.37   476.7  731.26   507.2  723.83   537.6  712.66   578.2     705
   638.8  681.39   739.9  658.03   800.5  637.26     836  628.82     851  626.97
     866  629.18   891.4  633.08  1063.2  633.08  1305.8  637.96  1346.2  652.15
  1376.5  659.37    1427  677.56  1487.7   688.2  1558.4  704.95  1598.4  704.82
  1758.4  696.17  1918.5   700.6  1958.5  707.14  2028.5  730.36  2128.5  749.51
#Mann= 3 , 0 , 0
       0     .06       0     836    .045       0     866     .06       0
Bank Sta=836,866
XS Rating Curve= 0 ,0
Exp/Cntr=0.3,0.1

Type RM Length L Ch R = 1 ,75647.4 ,602.8,608.7,614.6
XS GIS Cut Line= 4
     1588080.191      460551.634     1588815.876      461116.855
     1589479.787      461520.585     1590125.754      461475.726
#Sta/Elev= 30
    10.1   827.8    60.5  823.71   110.9  825.49   231.9  852.93   272.3  853.08
   292.4  848.24   312.6  839.33   373.1  825.51   433.6  804.11   524.4  782.39
   685.7  760.82     716  752.83   857.2  727.53   877.3  721.11  1089.2  634.66
  1149.8  631.74  1391.9  631.78  1427.4  627.74  1442.4  625.72  1457.4  627.29
  1533.2  648.08  1704.8  706.74  1735.1  711.03  1795.8  731.69  1866.7  749.36
  1947.6  774.17  2079.1  789.46  2220.8  815.46  2311.8  821.91  2352.3  831.29
#Mann= 3 , 0 , 0
       0     .06       0  1427.4    .045       0  1457.4     .06       0
Bank Sta=1427.4,1457.4
XS Rating Curve= 0 ,0
Exp/Cntr=0.3,0.1

Type RM Length L Ch R = 1 ,75038.8 ,770.2,759.4,748.5
XS GIS Cut Line= 4
     1587416.281      460847.702     1588501.864      461224.517
     1588824.848      461771.794      1589919.21      461880.744
#Sta/Elev= 30
    10.1  871.72    40.3  873.94    60.5  869.71   211.7  814.79   393.1   764.6
   453.6  735.39   564.5  741.16   715.7  701.97   735.8   700.2   806.4  724.34
   846.7  733.27   977.8  744.37  1108.8  743.05  1149.1  733.61  1330.7   635.5
    1467  629.49 1482.03  625.54    1497  626.88  1532.4  632.46  1613.1  636.74
  1633.3  647.06  1784.6  701.37  1925.9   734.1  2097.4  757.89  2198.3  754.21
  2258.8  757.83  2410.2  780.68  2531.2  806.75  2682.6  815.86  2884.4  842.63
#Mann= 3 , 0 , 0
    10.1     .06       0    1467    .045       0    1497     .06       0
Bank Sta=1467,1497
XS Rating Curve= 0 ,0
Exp/Cntr=0.3,0.1

Type RM Length L Ch R = 1 ,74279.4 ,1197.4,1187.8,1178.3
XS GIS Cut Line= 4
     1586662.652      462211.411     1587721.321      461969.173
     1588860.553      461954.029      1589901.46      462040.947
#Sta/Elev= 30
    10.1  814.29    30.4  816.71    50.7  813.71     203  780.75   345.1  809.81
   497.3  816.34     680  833.87   751.1  844.88   842.4  846.46   893.2  852.31
  1136.4  765.79  1307.8   673.2  1378.4  643.03  1418.8  634.19  1655.8  626.95
 1670.84  625.44  1685.8  628.42    1812  636.24  1842.2  650.35  1892.6  658.53
  1993.5  690.79  2296.3  745.22  2367.3  746.17  2438.3   737.5  2590.4  736.18
  2651.3  743.35  2762.8  765.19  3016.4  819.92  3138.1  819.37  3269.9  802.92
#Mann= 3 , 0 , 0
    10.1     .06       0  1655.8    .045       0  1685.8     .06       0
Bank Sta=1655.8,1685.8
XS Rating Curve= 0 ,0
Exp/Cntr=0.3,0.1

Type RM Length L Ch R = 1 ,73091.5 ,1190.5,1195.5,1200.3
XS GIS Cut Line= 4
      1588235.05      463170.542     1588753.074      462785.604
     1589183.719      462175.524     1589659.223      462121.693
#Sta/Elev= 30
    10.1  698.82    30.3  705.17    50.4  709.62    90.8  713.82   312.6  711.62
   342.9  708.55   373.1  703.91   443.7  687.48   494.1   672.5   514.3  665.41
   544.5  652.57   554.6  651.37   645.4  643.91   857.3  632.25   968.3  629.18
  1129.8  629.29  1155.1  626.97 1169.95  625.37  1185.1  627.85  1210.5  634.55
  1230.7  637.39  1271.1  649.06  1392.1  688.46  1461.9  713.37  1491.8  722.44
  1531.7   732.5  1571.6  740.66  1671.3  757.86  1751.1  774.16  1870.7  785.01
#Mann= 3 , 0 , 0
    10.1     .06       0  1155.1    .045       0  1185.1     .06       0
Bank Sta=1155.1,1185.1
XS Rating Curve= 0 ,0
Exp/Cntr=0.3,0.1

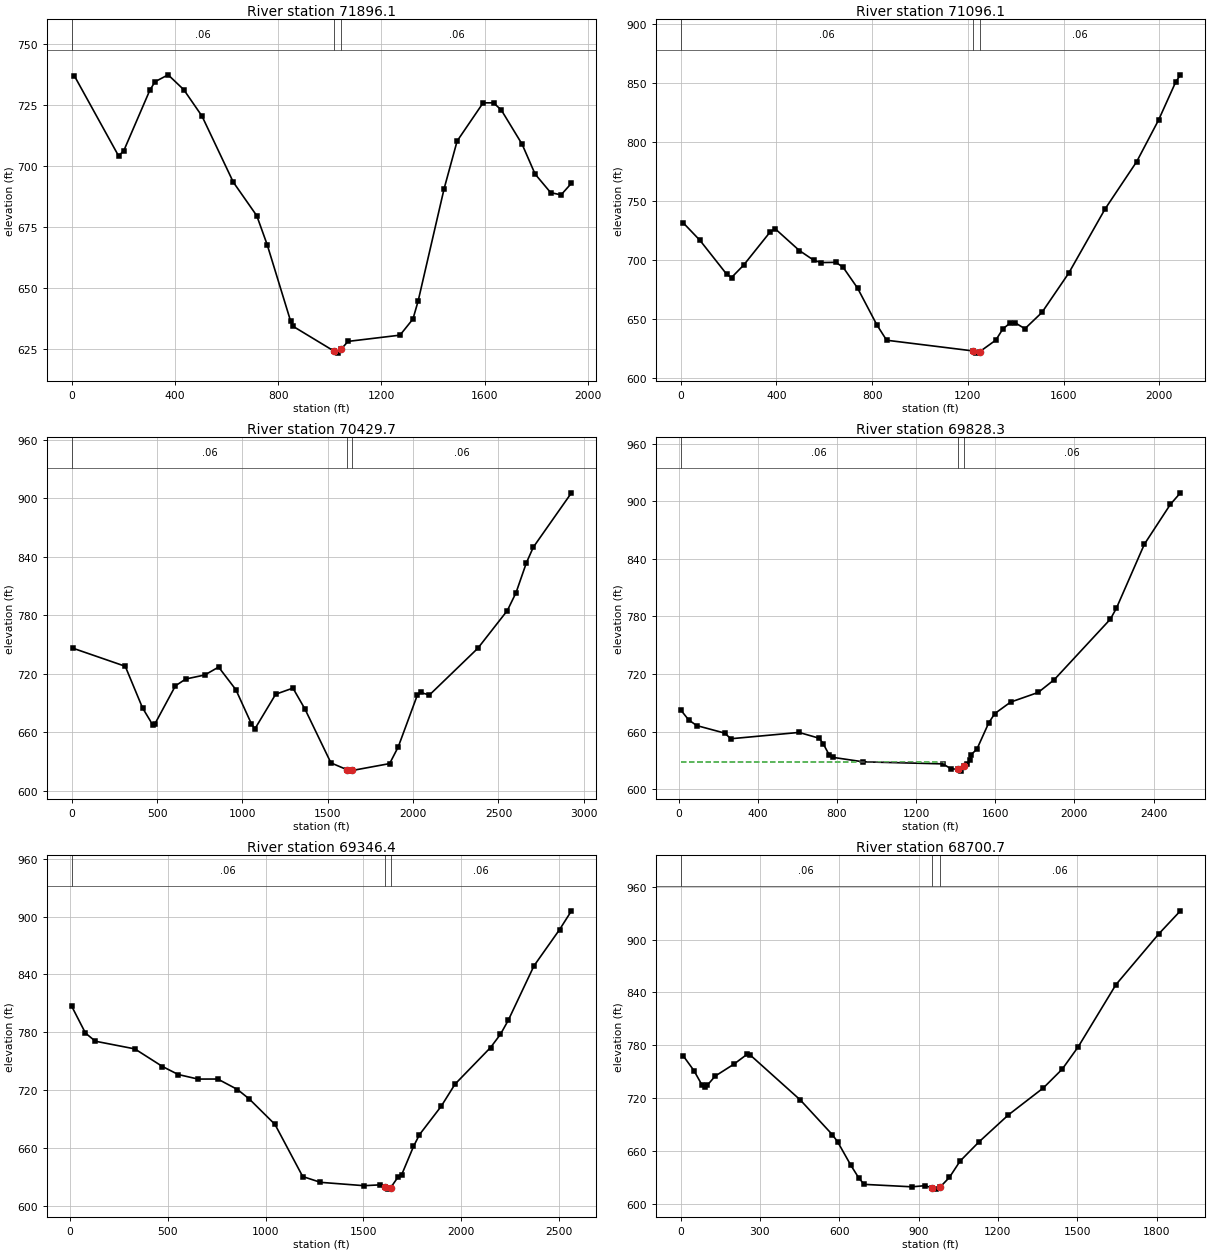
Type RM Length L Ch R = 1 ,71896.1 ,795.6,800,805.8
XS GIS Cut Line= 3
     1588582.696      463711.564     1589450.087      463154.852
     1590204.465      462652.554
#Sta/Elev= 30
    10.1   737.2   181.9  704.28   202.1  706.44   303.1  731.26   323.3  734.73
   373.9  737.54   434.5  731.45   505.2  720.59   626.5  693.51   717.4  679.76
   757.9  667.84   848.8  636.46   858.9  634.36  1015.7  624.32  1030.7  623.42
  1045.7  625.19    1071  628.23  1272.4  630.79  1322.7  637.41  1342.8  644.81
  1443.5  690.88  1493.9   710.4  1594.6  726.05  1634.9  726.06  1665.1   723.1
  1745.7  709.08    1796  696.85  1856.4  689.22  1896.7  688.32    1937  693.09
#Mann= 3 , 0 , 0
       0     .06       0  1015.7    .045       0  1045.7     .06       0
Bank Sta=1015.7,1045.7
XS Rating Curve= 0 ,0
Exp/Cntr=0.3,0.1

Type RM Length L Ch R = 1 ,71096.1 ,664.2,666.4,676.7
XS GIS Cut Line= 3
     1588676.371      463873.065     1589899.447      463699.968
      1590751.71      463676.001
#Sta/Elev= 30
    10.1   731.4      81  716.36   192.4  687.67   212.6  684.83   263.3  695.38
   374.6  723.64   394.9  726.22   496.1  707.74   556.9  699.43   587.3  697.54
     648  697.75   678.4  693.68   739.1  675.92   820.1  644.61   860.6  631.67
  1220.3  622.63  1235.3  620.73  1250.3  622.06  1316.5  631.73  1346.9  641.45
  1377.4  646.35  1397.7  646.44  1438.3  641.44  1509.3  655.21    1621  688.48
  1773.2  743.03  1905.2  783.14  1996.5   818.4  2067.6  850.44  2087.9  856.79
#Mann= 3 , 0 , 0
       0     .06       0  1220.3    .045       0  1250.3     .06       0
Bank Sta=1220.3,1250.3
XS Rating Curve= 0 ,0
Exp/Cntr=0.3,0.1

Type RM Length L Ch R = 1 ,70429.7 ,612.3,601.4,590.5
XS GIS Cut Line= 4
     1588044.304      464292.861     1589300.352      464068.567
     1590018.093      464463.325      1590738.23      464045.833
#Sta/Elev= 30
    10.1  746.25   313.9  727.89   415.2  685.18   475.9   667.5   486.1  668.31
   607.6  707.81   668.3  714.85   779.7  718.95   860.7  727.07     962  703.82
  1053.1  668.77  1073.4  663.76  1194.9  699.21  1296.1  705.51  1366.9   683.9
  1518.6  628.81  1614.9   621.7  1629.9  620.37  1644.9  621.08  1862.5   628.1
    1913  645.29  2024.3  698.13  2044.5  701.03  2095.1  698.38  2379.3  746.41
  2551.9  785.06  2602.6  803.28  2663.5  834.03  2704.1  850.03  2927.5  905.76
#Mann= 3 , 0 , 0
       0     .06       0  1614.9    .045       0  1644.9     .06       0
Bank Sta=1614.9,1644.9
XS Rating Curve= 0 ,0
Exp/Cntr=0.3,0.1

Type RM Length L Ch R = 1 ,69828.3 ,488,481.9,475.8
XS GIS Cut Line= 5
     1588924.972      465657.456     1589279.345       464905.02
     1589924.983      464492.394     1590143.433      464472.976
     1590784.217       464147.73
#Sta/Elev= 30
    10.1  682.79    50.7  672.29    91.3  666.36   233.3  658.48   263.7  652.62
   608.6  659.21     710  653.19   730.3  647.63   760.7  635.87     781   633.2
   932.5   628.6  1335.8  626.45 1374.56  621.52  1411.5  620.62  1426.5   618.9
  1441.5   624.3 1458.97  625.81 1474.35  630.54    1477  635.89  1507.2  641.69
  1567.7  669.38  1597.9  678.86  1677.7   690.8  1817.3  700.88  1898.2  714.14
  2181.6  777.15    2212  788.42  2353.7  855.25  2485.2  896.78  2535.9  908.79
#Mann= 3 , 0 , 0
    10.1     .06       0  1411.5    .045       0  1441.5     .06       0
#XS Ineff= 2 , 0
         1343.12  628.24
Permanent Ineff=
       F       F
Bank Sta=1411.5,1441.5
XS Rating Curve= 0 ,0
Exp/Cntr=0.3,0.1

Type RM Length L Ch R = 1 ,69346.4 ,642.6,645.7,649.5
XS GIS Cut Line= 4
     1589192.691      466042.356     1589973.234      465342.558
     1590295.916       464579.53     1590856.078      464184.695
#Sta/Elev= 30
    10.1  807.09    80.6  779.18     131  770.74   332.6  762.77   473.8  744.48
   554.4  736.16   655.2  731.46     756  731.49   856.8  720.63   917.3  710.74
  1048.3  684.38  1189.8  630.31 1280.51   624.3    1503  620.81  1583.8  621.67
  1609.2  619.06  1624.2  617.24  1639.2  618.85 1675.76  629.53  1694.9  632.08
  1755.5  661.49  1785.8  673.72  1896.9   703.2  1967.5  726.19  2148.9   764.2
  2199.3  777.85  2239.6  792.55  2370.6  848.94  2501.6  886.66  2562.1  906.05
#Mann= 3 , 0 , 0
    10.1     .06       0  1609.2    .045       0  1639.2     .06       0
Bank Sta=1609.2,1639.2
XS Rating Curve= 0 ,0
Exp/Cntr=0.3,0.1

Type RM Length L Ch R = 1 ,68700.7 ,856.7,861.4,865.4
XS GIS Cut Line= 3
     1590009.121      466006.469      1590638.44       465274.11
     1591285.845      464613.891
#Sta/Elev= 30
    10.1  768.06    50.3  751.49    80.5  735.28    90.5  733.22   100.6  734.69
   130.8  745.19   201.2  758.64   251.5   769.9   261.5  769.55   452.6  718.15
   573.3  678.95   593.4  670.91   643.7  644.16   673.9  629.68     694  622.43
   875.1  619.65   925.4  620.98   950.6  618.31   965.6  617.03   980.6  619.09
  1016.4  630.25  1057.1  648.86  1128.2   670.5    1240  701.27  1372.1  731.82
  1443.2  753.04  1504.2  778.59  1646.4  848.87    1809  906.59  1890.3  932.56
#Mann= 3 , 0 , 0
       0     .06       0   950.6    .045       0   980.6     .06       0
Bank Sta=950.6,980.6
XS Rating Curve= 0 ,0
Exp/Cntr=0.3,0.1

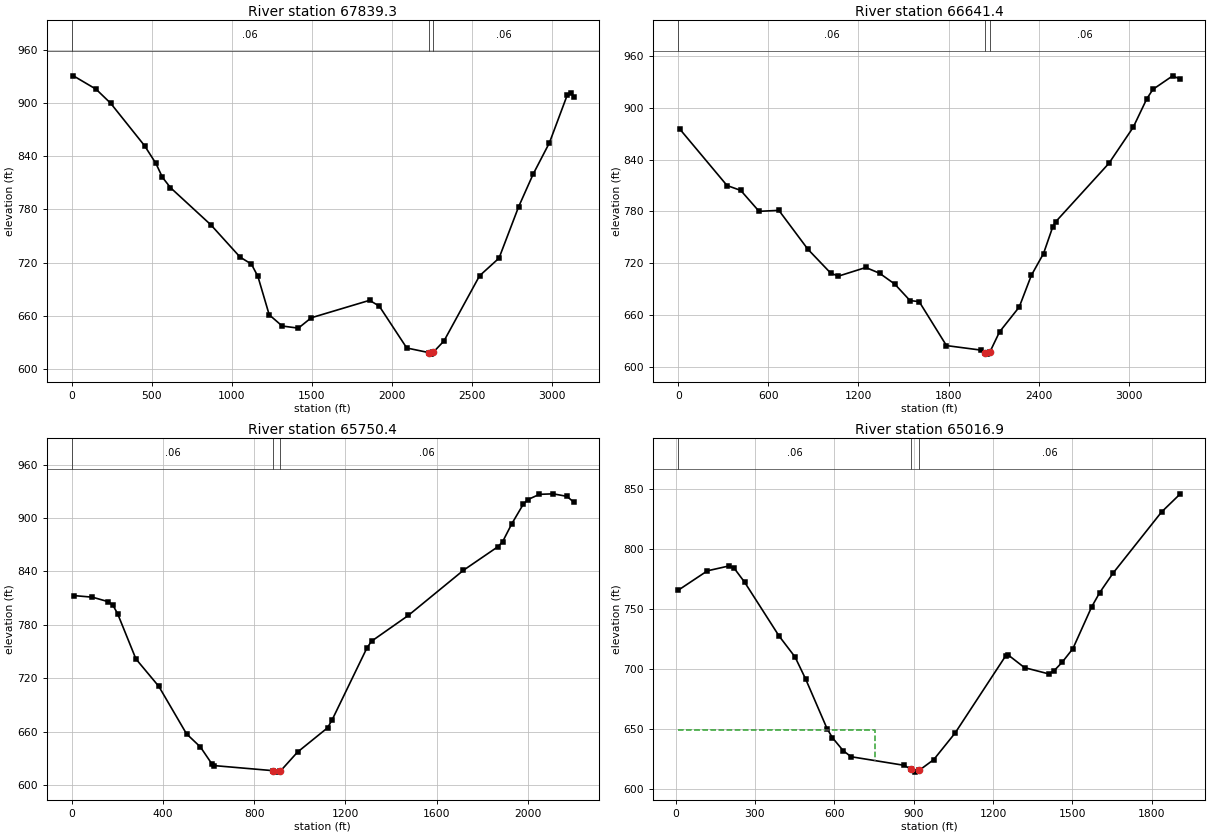
Type RM Length L Ch R = 1 ,67839.3 ,1188.8,1197.9,1207.1
XS GIS Cut Line= 4
     1589076.058      466544.775     1590739.148      466073.656
     1591588.153      465719.372      1592054.88       465578.38
#Sta/Elev= 30
    10.1  930.38   151.6  915.34   242.6  899.55   454.9  851.64   525.6  831.73
   566.1  816.14   616.6  804.43   869.3  762.49  1051.3  726.26    1122  718.38
  1162.5  704.54  1233.2  661.32  1314.1  648.65  1415.2  646.25    1496  657.93
    1860  677.56  1920.6  671.07  2092.5   623.9  2229.1  618.74  2244.1  616.99
  2259.1  619.29    2325  631.85  2547.4  705.25  2668.8  725.09  2790.7  782.73
  2882.1  819.75  2983.7  855.03  3095.4  908.97  3115.7  911.33  3136.1  906.87
#Mann= 3 , 0 , 0
       0     .06       0  2229.1    .045       0  2259.1     .06       0
Bank Sta=2229.1,2259.1
XS Rating Curve= 0 ,0
Exp/Cntr=0.3,0.1

Type RM Length L Ch R = 1 ,66641.4 ,880.1,891,855.3
XS GIS Cut Line= 4
     1589641.279      468007.173     1590628.173      466742.154
     1591256.197       467127.94     1592151.556      466677.995
#Sta/Elev= 30
    10.2  875.33     325  809.96   416.3  804.31   538.2  780.11   670.2  781.21
   863.1  736.29  1015.5  708.56  1066.2  705.08    1249   715.1  1340.4  708.49
    1442  695.88  1543.5  676.81  1604.4  675.61  1786.2  624.72  2018.4  619.43
  2043.8  615.68  2058.8  614.84  2073.8  616.74  2139.6  640.57  2270.8  669.34
  2351.6  706.06  2432.6  731.26  2493.3  761.76  2513.6  768.03  2867.8  835.61
  3029.8  877.36  3120.9  910.55  3161.4  921.28  3292.9  936.92  3343.5  932.98
#Mann= 3 , 0 , 0
       0     .06       0  2043.8    .045       0  2073.8     .06       0
Bank Sta=2043.8,2073.8
XS Rating Curve= 0 ,0
Exp/Cntr=0.3,0.1

Type RM Length L Ch R = 1 ,65750.4 ,738.1,733.6,729
XS GIS Cut Line= 4
     1590372.971       468079.26     1590699.948      467845.681
     1591489.463      467388.121     1592172.784      466822.002
#Sta/Elev= 30
      10  812.88    90.4  811.11   160.7     806   180.8  801.89   200.9  792.65
   281.3  741.77   381.7  710.96   503.2  657.68   564.1  642.92   614.8  623.79
   624.9  622.02   883.7  616.31   898.7   614.7   913.7   615.5   989.9  637.17
  1121.7  664.46    1142  673.53  1294.1  753.98  1314.4  761.67  1475.7  790.59
  1717.7  841.34    1869  867.82  1889.1  873.28  1929.5  893.47  1979.9  915.44
  2000.1  920.66  2050.5  926.56    2111  927.14  2171.5   924.3  2201.7  917.67
#Mann= 3 , 0 , 0
       0     .06       0   883.7    .045       0   913.7     .06       0
Bank Sta=883.7,913.7
XS Rating Curve= 0 ,0
Exp/Cntr=0.3,0.1

Type RM Length L Ch R = 1 ,65016.9 ,616.2,608.4,600.5
XS GIS Cut Line= 4
     1590928.329      468603.572     1591336.943       468500.62
     1591767.588      467782.879     1591991.882      467172.799
#Sta/Elev= 30
      10  765.87   120.4  782.05   200.7  786.04   220.7  784.44   260.9  772.58
   391.3  727.67   451.6  710.25     492   691.7   572.7  650.49   592.8  642.99
   633.2  632.23   663.4  627.07   865.1  619.87   890.4  616.53   905.4  614.23
   920.4  615.62     976  624.64  1056.7  646.77  1248.3  711.22  1258.4  711.76
  1319.3  701.33  1410.8  696.13  1431.1  698.76  1461.5  705.79  1502.2  717.16
  1573.3  752.01  1603.7  763.92  1654.5  780.22  1837.3  831.03  1908.4  846.22
#Mann= 3 , 0 , 0
      10     .06       0   890.4    .045       0   920.4     .06       0
#XS Ineff= 2 , 0
          753.42  649.41
Permanent Ineff=
       F       F
Bank Sta=890.4,920.4
XS Rating Curve= 0 ,0
Exp/Cntr=0.3,0.1