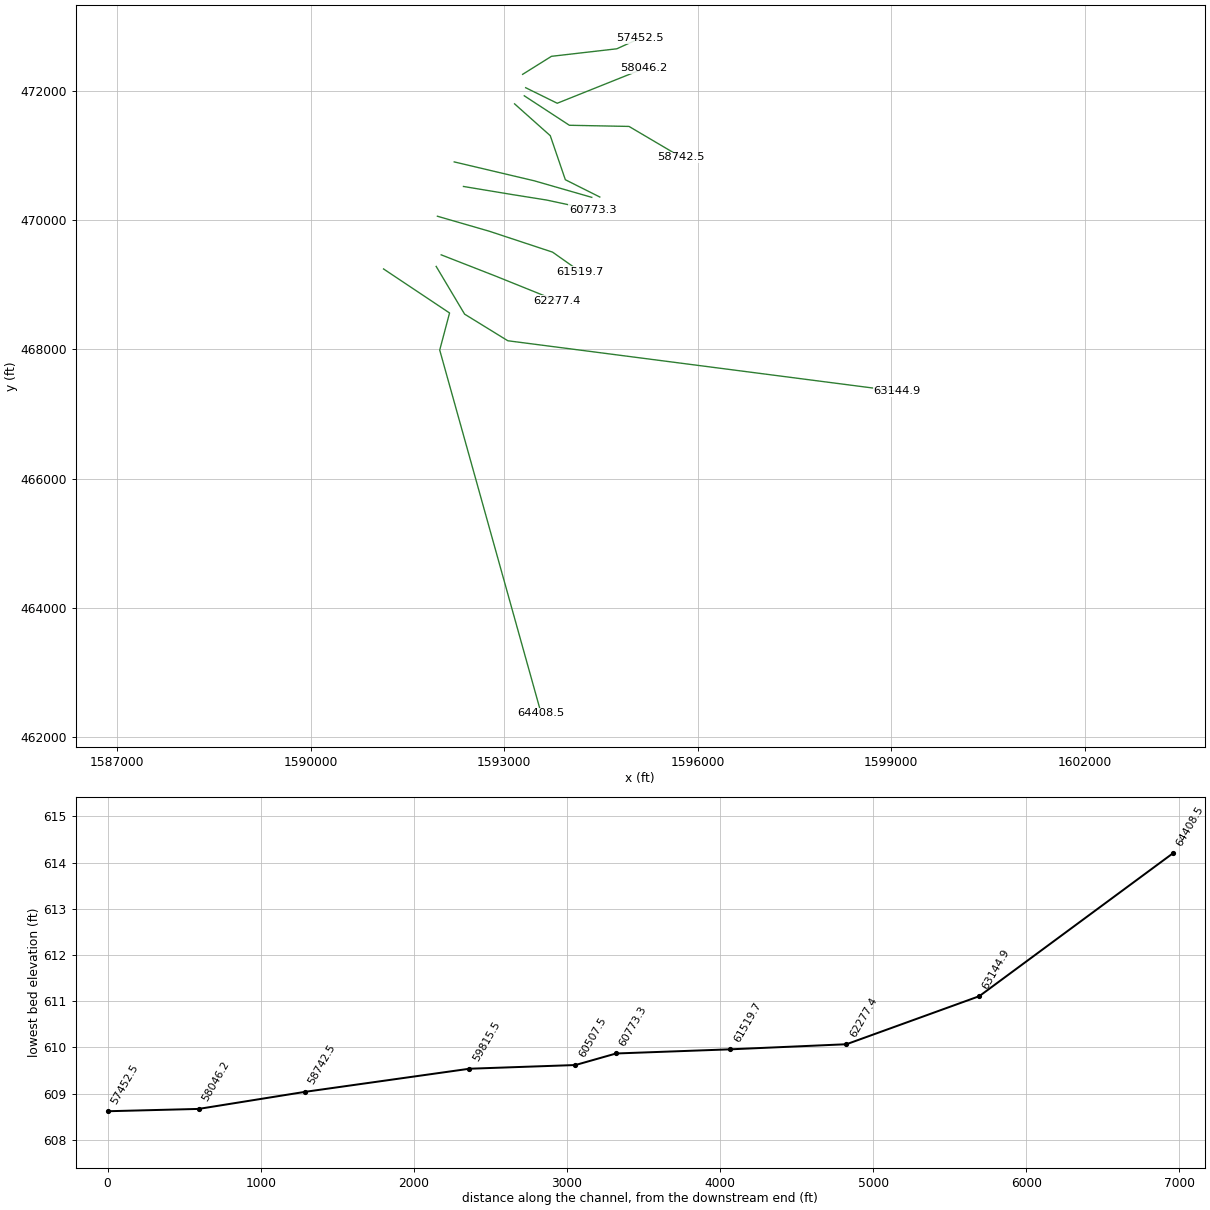
HEC-RAS study BEECHFK.prj: BEECHFK

--- BEECHFK.g01 (geometry) --- (continued)

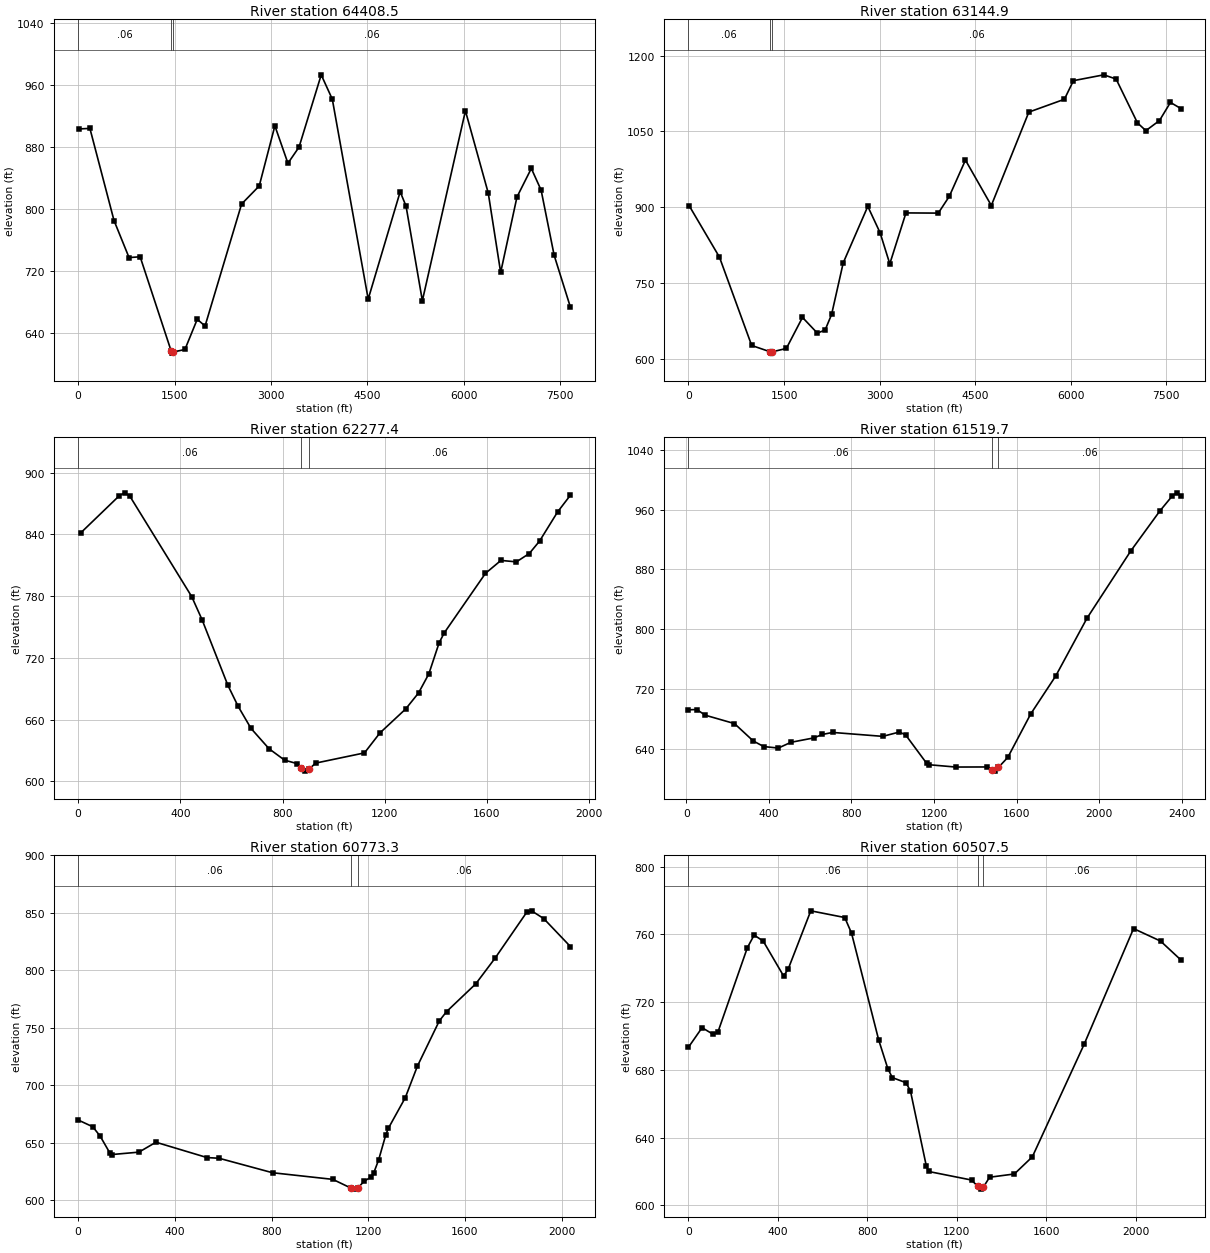
Type RM Length L Ch R = 1 ,64408.5 ,1250.5,1263.6,1276.7
XS GIS Cut Line= 4
     1591130.592      469245.277     1592153.374      468563.423
     1592000.854       467989.23     1593572.987      462363.328
#Sta/Elev= 30
    10.2   903.1   182.9  903.79   558.7  784.97   792.4   737.3   965.1  738.38
  1445.8   617.5  1460.8   614.2  1475.8  615.55  1662.2  618.88  1853.8  657.78
  1975.7  649.17  2544.6  806.36  2818.9  829.61  3062.7  907.11  3265.9  858.86
  3438.6  879.66    3784  972.84  3956.7  941.45  4515.5   683.8  5013.3  822.17
  5104.7  803.65  5358.7  681.76  6029.2  926.45  6384.7  820.45  6577.8  718.16
  6831.7  815.39  7055.2   852.2  7207.6  824.23  7410.8   740.2  7664.8  673.17
#Mann= 3 , 0 , 0
       0     .06       0  1445.8    .045       0  1475.8     .06       0
Bank Sta=1445.8,1475.8
XS Rating Curve= 0 ,0
Exp/Cntr=0.3,0.1

Type RM Length L Ch R = 1 ,63144.9 ,865.8,867.5,869.1
XS GIS Cut Line= 4
     1591945.901      469284.781      1592386.64      468545.479
     1593056.444      468133.384     1599085.362      467353.478
#Sta/Elev= 30
    10.1  902.97     486   801.1   991.8  626.29  1279.2  613.87  1294.2  611.11
  1309.2   613.5  1536.2  620.41  1789.2  681.76  2022.6  650.67  2144.4  656.85
  2245.9  687.56  2428.6  789.81  2814.2  901.44  3007.1  849.34  3159.3  787.79
    3413  888.56  3920.5  888.16    4093  921.26  4346.7  993.06  4752.7  903.21
  5341.3 1088.01  5899.5 1113.42  6041.6 1150.25  6518.6 1161.79  6711.4  1153.4
  7046.3 1066.67  7178.2 1051.33  7391.4 1071.29  7563.9 1107.17  7726.3 1095.13
#Mann= 3 , 0 , 0
       0     .06       0  1279.2    .045       0  1309.2     .06       0
Bank Sta=1279.2,1309.2
XS Rating Curve= 0 ,0
Exp/Cntr=0.3,0.1

Type RM Length L Ch R = 1 ,62277.4 ,757.3,757.7,758.3
XS GIS Cut Line= 3
     1592023.484      469463.979     1592851.465      469140.838
     1593814.717      468753.333
#Sta/Elev= 30
    10.1  841.57   161.6   877.8   181.8  880.49     202  877.36   444.4  779.69
   484.8  757.33   585.8   693.6   626.2  673.01   676.7  651.54   747.4  631.78
     808  620.74   858.5  617.27   873.8  612.68   888.8  610.07   903.8  611.93
   929.1  617.84  1120.7  627.78  1181.1  647.14  1281.9  670.44  1332.3  686.01
  1372.7  704.59    1413  734.81  1433.1  744.45  1594.4  802.27  1654.9  814.82
  1715.4  813.41  1765.8  821.51  1806.1  833.61  1876.7  861.94  1927.1  878.27
#Mann= 3 , 0 , 0
       0     .06       0   873.8    .045       0   903.8     .06       0
Bank Sta=873.8,903.8
XS Rating Curve= 0 ,0
Exp/Cntr=0.3,0.1

Type RM Length L Ch R = 1 ,61519.7 ,745.5,746.4,746.7
XS GIS Cut Line= 4
     1591964.967      470061.708     1592772.426      469828.442
     1593750.349      469505.458     1594179.879      469202.713
#Sta/Elev= 30
    10.1   692.1    50.6  692.44    91.1  684.89   232.9  673.65     324  650.36
   374.7  642.86   445.6  640.85   506.3  648.54   617.7  654.46   658.2  659.02
   708.8  661.78   951.5  656.52  1032.3  662.34  1062.6  658.39  1163.6  620.66
  1173.7  618.58  1304.9  615.43  1456.4  615.54  1481.8  611.49 1497.01  609.96
  1511.8  614.87  1557.4  628.29  1668.4  686.43  1789.6   737.3  1941.1  814.65
  2153.3  904.78  2294.8  958.51  2355.4  978.77  2375.6  982.68  2395.9  979.05
#Mann= 3 , 0 , 0
    10.1     .06       0  1481.8    .045       0  1511.8     .06       0
Bank Sta=1481.8,1511.8
XS Rating Curve= 0 ,0
Exp/Cntr=0.3,0.1

Type RM Length L Ch R = 1 ,60773.3 ,277.9,265.8,254.1
XS GIS Cut Line= 4
     1592368.938      470522.576     1593122.856      470397.594
     1593655.034       470312.93     1594372.668      470159.727
#Sta/Elev= 30
       0  669.95    60.3  664.07    90.5   656.1   130.7  641.44   140.8  639.95
   251.4  642.01   321.8  650.62   532.9  637.31   583.2  636.68   804.1  624.12
  1053.6  618.35  1130.9  610.55  1143.4  609.87  1155.9  610.62  1183.3  616.77
  1213.3  620.53  1223.2  624.14  1243.2  635.29  1273.1  657.28  1283.1  662.61
  1353.3  689.28  1403.6  716.76  1494.1  756.04  1524.2  764.13  1644.9  788.22
  1725.3  810.69  1855.9  850.49    1876  851.71  1926.3  844.95  2036.9   820.6
#Mann= 3 , 0 , 0
       0     .06       0  1130.9    .045       0  1155.9     .06       0
Bank Sta=1130.9,1155.9
XS Rating Curve= 0 ,0
Exp/Cntr=0.3,0.1

Type RM Length L Ch R = 1 ,60507.5 ,701.1,692.1,683
XS GIS Cut Line= 3
     1592225.659      470903.011     1593467.811       470609.96
     1594357.415       470354.07
#Sta/Elev= 30
       0  693.38    60.8  704.91   111.4  700.92   131.7  702.33   263.4  752.14
   293.7  759.58   334.3  756.01   425.4  735.43   445.7  739.42     547  773.89
   698.9  769.94   729.3   760.7   850.8  697.63   891.4  680.81   911.6  675.45
   972.4  672.46   992.6  667.67  1063.5  623.45  1073.7  620.04  1266.1  614.98
  1293.9  611.21 1306.48  609.62  1318.9  610.78  1346.7  616.64  1457.4  618.56
  1537.9  628.68  1769.3  695.03  1990.6  763.41  2111.4  756.03  2201.9  744.94
#Mann= 3 , 0 , 0
       0     .06       0  1293.9    .045       0  1318.9     .06       0
Bank Sta=1293.9,1318.9
XS Rating Curve= 0 ,0
Exp/Cntr=0.3,0.1

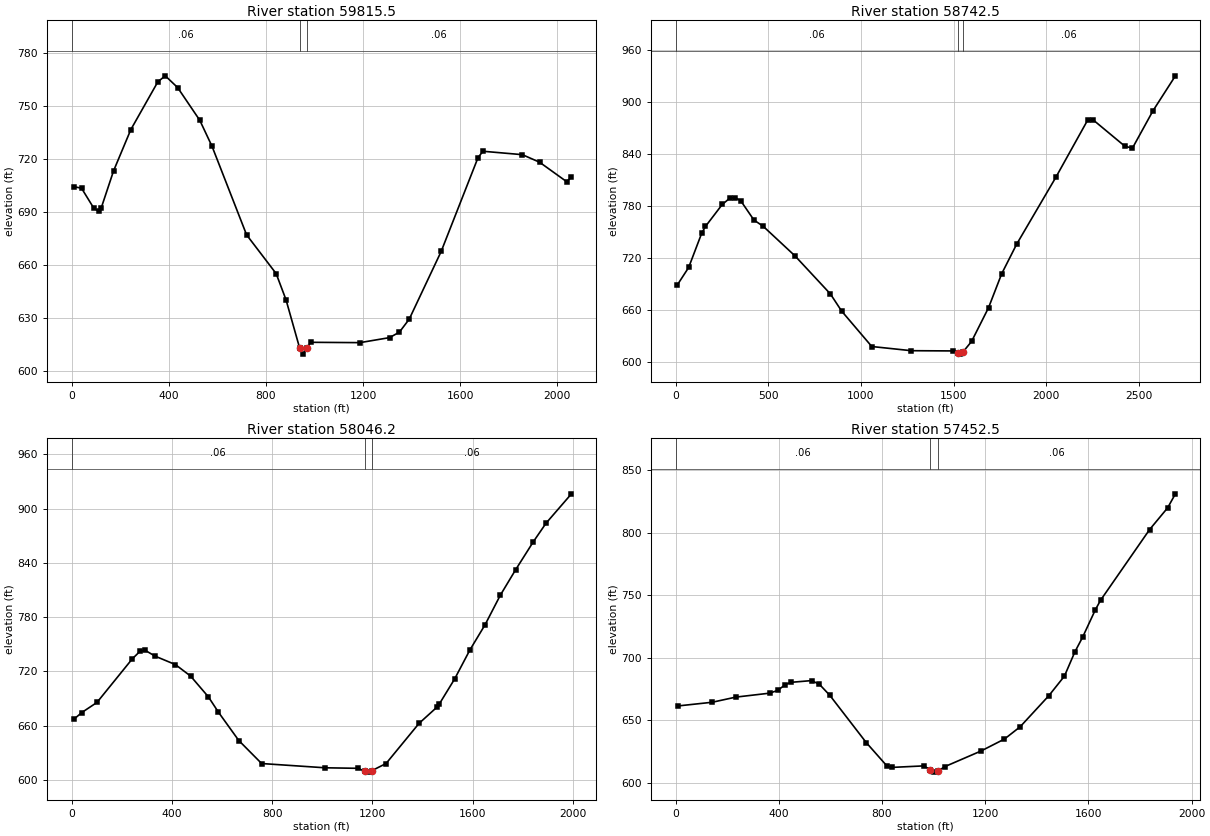
Type RM Length L Ch R = 1 ,59815.5 ,1060.9,1073,1085.1
XS GIS Cut Line= 4
     1593161.147      471801.593     1593714.462      471308.784
     1593947.727      470626.929     1594481.804      470359.425
#Sta/Elev= 30
    10.2   704.4    40.6  703.59    91.4  692.21   111.7  690.56   121.8  692.36
   172.6  713.38   243.6  736.75   355.3  763.92   385.7  767.26   436.5  760.62
   527.8  742.07   578.6  727.21   720.7  677.12   842.5  655.16   883.1  640.32
   939.1  613.04   954.1  609.54   969.1  613.06   984.6  616.24  1187.6  616.05
  1309.4  618.89    1350  621.98  1390.6  629.35  1522.4   667.8  1674.2  720.96
  1694.5  724.51  1856.5  722.58  1927.3  718.33  2038.7  707.32  2058.9   709.8
#Mann= 3 , 0 , 0
       0     .06       0   939.1    .045       0   969.1     .06       0
Bank Sta=939.1,969.1
XS Rating Curve= 0 ,0
Exp/Cntr=0.3,0.1

Type RM Length L Ch R = 1 ,58742.5 ,692.3,696.3,700.3
XS GIS Cut Line= 4
     1593311.396       471926.58      1594010.53      471470.275
     1594934.622      471452.332     1595742.081      470976.828
#Sta/Elev= 30
    10.1  689.17    70.4  709.03   140.8  748.58   160.9  756.34   251.5   781.7
   291.7  788.91   321.9   789.7   352.1  785.77   422.5  763.77   472.8  756.49
   643.8  722.45   834.9   678.5   895.8  658.68  1058.3  617.82  1271.6     613
  1495.1  612.73  1520.7  609.91  1535.7  609.04  1550.7  611.65  1596.6  623.69
    1688  662.53  1759.1  701.81  1839.7  735.86  2051.3   813.1  2222.6  878.97
  2252.9  879.25  2424.1  848.85  2464.5  846.77  2575.3  889.87  2696.2  930.17
#Mann= 3 , 0 , 0
       0     .06       0  1520.7    .045       0  1550.7     .06       0
Bank Sta=1520.7,1550.7
XS Rating Curve= 0 ,0
Exp/Cntr=0.3,0.1

Type RM Length L Ch R = 1 ,58046.2 ,596.7,593.7,590.7
XS GIS Cut Line= 3
     1593332.698      472052.061     1593822.123      471811.203
     1595167.888      472349.509
#Sta/Elev= 30
    10.1   667.4    40.4  674.54     101   685.7   242.4  734.01   272.7  742.19
   292.9  743.38   333.3  736.84   414.2  727.53   474.8  714.82   545.5  691.96
     586  674.87   667.1  643.62   758.3  618.17  1011.7  613.46  1143.5  612.88
    1169   609.6    1184  608.67    1199  610.41    1255   618.2  1386.8  662.62
  1457.7   680.4  1467.8  684.12  1528.7  711.69  1589.5  743.69  1650.3  771.66
  1711.1  804.27  1771.9  832.29  1842.9  863.38  1893.6  883.87  1994.9  916.29
#Mann= 3 , 0 , 0
       0     .06       0    1169    .045       0    1199     .06       0
Bank Sta=1169,1199
XS Rating Curve= 0 ,0
Exp/Cntr=0.3,0.1

Type RM Length L Ch R = 1 ,57452.5 ,57426.3,57452.1,57479.79
XS GIS Cut Line= 4
     1593285.765      472258.789     1593732.405      472537.916
     1594746.215      472654.549     1595100.601      472816.465
#Sta/Elev= 30
    10.1  661.53   141.8  664.45     233  668.55   364.6  671.72     395  673.88
   425.4  678.53   445.7  680.35   526.7  681.75     557  678.85   597.4  670.03
   738.9   632.2   819.7  613.35   839.9  612.41   961.2   613.6   986.6   610.6
  1001.6  608.62  1016.6  609.28    1042   612.9  1183.4  625.49  1274.4  635.06
    1335  644.82  1446.1  669.64  1506.8  685.36  1547.2  704.69  1577.2  716.44
  1627.1  738.56  1647.1  746.06  1836.9  802.47  1906.8  819.83  1936.8  830.99
#Mann= 3 , 0 , 0
       0     .06       0   986.6    .045       0  1016.6     .06       0
Bank Sta=986.6,1016.6
XS Rating Curve= 0 ,0
Exp/Cntr=0.3,0.1

Chan Stop Cuts=-1
Use User Specified Reach Order=0